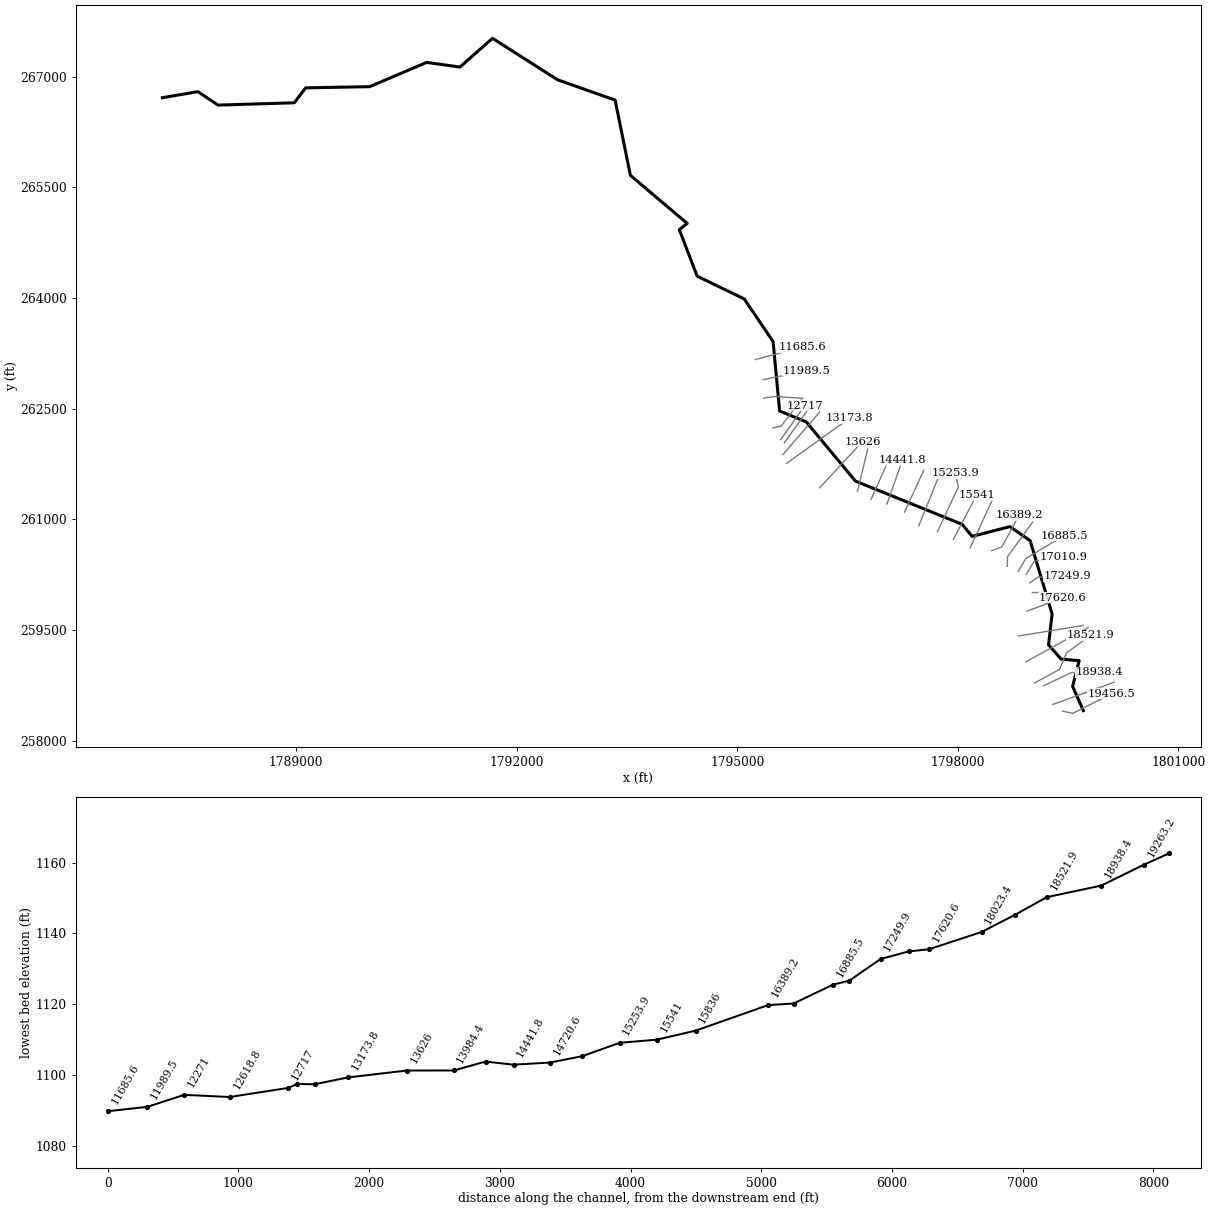
--- SIMPSONCK.prj (project) ---

Proj Title=SIMPSONCK
Current Plan=p01
Default Exp/Contr=0,0
English Units
Geom File=g01
Flow File=f01
Plan File=p01
BEGIN DESCRIPTION:
END DESCRIPTION:
DSS Export Rating Curves= 0
DSS Export Rating Curve Sorted= 0
DSS Export Volume Flow Curves= 0
DXF OffsetX= 0
DXF OffsetY= 0
DXF ScaleX= 0
DXF ScaleY= 0

--- SIMPSONCK.p01 (plan) ---

Plan Title=Floodplain
Program Version=4.00
Geom File=g01
Flow File=f01
K Sum by GR=0
Std Step Tol=0.01
Critical Tol=0.01
Num of Std Step Trials=20
Max Error Tol=0.3
Flow Tol Ratio=0.001
Split Flow NTrial=30
Split Flow Tol=0.02
Split Flow Ratio=0.02
Log Output Level=0
Friction Slope Method=1
Unsteady Friction Slope Method=2
Unsteady Bridges Friction Slope Method=1
Global Log Level=0
CheckData=False
Run HTab=0
Run UNet=0
Run PostProcess=0
UNET Theta=0
UNET Theta Warmup=0
UNET ZTol=0
UNET ZSATol=0
UNET MxIter=0
UNET MaxInSteps=0
UNET DtIC=0
UNET DtMin=0
UNET MaxCRTS=0
UNET WFStab=0
UNET SFStab=0
UNET WFX=0
UNET SFX=0
UNET DSS MLevel=0
UNET DZMax Abort=0
UNET Convert EG Bridges=0
UNET Use Existing IB Tables=0
UNET Froude Limit=0
UNET Froude Power=0
Write IC File=0
Echo Input=False
Echo Output=False
Write Detailed=0

--- SIMPSONCK.f01 (steady flow) ---

Flow Title=NFF Regression Equation
Program Version=4.10
Number of Profiles= 1
Profile Names=P100yr
River Rch & RM=SIMPSONCK,Main            ,19456.5
865.6017
River Rch & RM=SIMPSONCK,Main            ,18938.4
1125.273
River Rch & RM=SIMPSONCK,Main            ,17249.9
1172.697
River Rch & RM=SIMPSONCK,Main            ,15836
1301.466
River Rch & RM=SIMPSONCK,Main            ,13173.8
1383.817
River Rch & RM=SIMPSONCK,Main            ,12271
1759.013
River Rch & RM=SIMPSONCK,Main            ,8392
1853.774
River Rch & RM=SIMPSONCK,Main            ,598.6
2056.285
River Rch & RM=SIMPSONCK,Main            ,188.9
 2058.44
Boundary for River Rch & Prof#=SIMPSONCK,Main            , 1
Up Type= 0
Dn Type= 3
Dn Slope=0.00417
DSS Import GetInterval= 0
DSS Import GetPeak= 0
DSS Import FillOption= 0

--- SIMPSONCK.g01 (geometry) ---

Geom Title=USGS 10m DEM
Program Version=4.10

River Reach=SIMPSONCK       ,Main
Reach XY= 30
     1799707.511      258408.601     1799561.783      258736.854
     1799651.339      259085.915     1799406.308       259105.81
     1799234.466      259299.595     1799282.942      259718.975
     1798983.682      260712.247     1798708.536      260902.303
     1798193.241      260769.279     1798063.033      260930.737
     1796605.699      261519.858     1795937.837      262320.882
     1795575.896      262468.469     1795486.686       263409.18
     1795093.936      263987.682     1794454.359      264295.055
     1794211.001      264925.606     1794318.241      265010.599
     1793545.353      265661.937     1793337.442      266681.588
     1792557.238       266955.32      1791669.63      267518.237
     1791225.899      267129.339     1790773.507      267191.996
     1789998.401      266863.381     1789127.444      266847.322
     1788972.338      266644.979     1787935.986       266613.45
     1787661.695      266795.312     1787179.176      266713.949

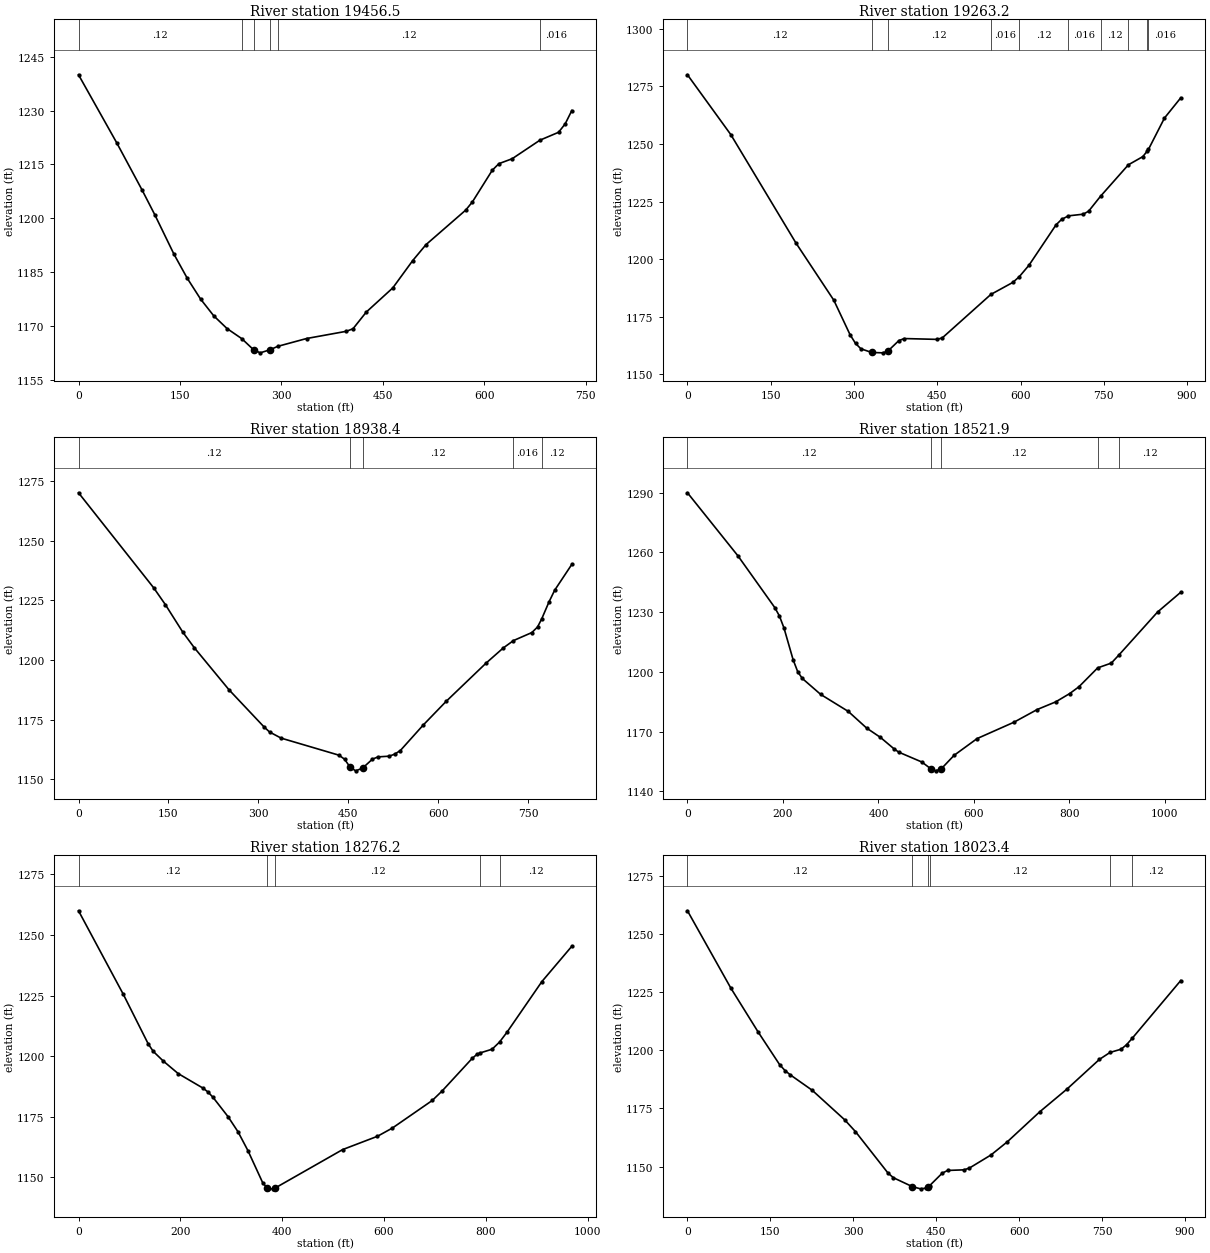
Type RM Length L Ch R = 1 ,19456.5 ,195.9,193.3,190.4
XS GIS Cut Line= 3
     1799426.203      258402.464     1799563.951      258371.308
     1800089.263      258635.841
#Sta/Elev= 30
       0 1239.97    56.5 1221.03    94.2 1207.82     113 1200.93   141.2    1190
   160.8 1183.32   180.4 1177.56     200 1172.86   219.6 1169.33  241.451166.512
   258.9 1163.41   268.7 1162.57   283.4 1163.45  294.611164.378   337.3 1166.56
   396.1 1168.57   405.9 1169.28   425.5 1173.92   464.7 1180.65   494.1 1188.24
   513.7 1192.67   572.5  1202.3   582.4 1204.58   611.8  1213.4   621.6 1215.23
   641.2  1216.6  682.231221.762   709.8 1223.96   719.6 1226.31   729.4 1230.01
#Mann= 6 ,-1 , 0
       0     .12       0  241.45    .016       0   258.9    .045       0
   283.4    .016       0  294.61     .12       0  682.23    .016       0
Bank Sta=258.9,283.4
XS Rating Curve= 0 ,0
Exp/Cntr=0.3,0.1

Type RM Length L Ch R = 1 ,19263.2 ,344.3,324.8,305.4
XS GIS Cut Line= 2
     1799293.215      258492.598     1800129.081      258794.537
#Sta/Elev= 30
       0    1280    78.1 1254.04   195.3 1207.08   263.7 1182.19     293 1167.21
   302.8 1163.46   312.5 1161.12     332 1159.53   351.6 1159.37   360.7 1160.04
   380.9 1164.69   390.6 1165.57   449.2 1165.21     459 1165.83   546.61184.706
     586  1189.9  597.481192.307   615.3 1197.38   664.1 1214.92   673.9 1217.22
  686.241218.791   712.9 1219.52   722.7 1220.81  744.161227.294  794.311240.938
   820.4  1244.5  827.881246.767  830.461247.609   859.4 1261.24   888.7    1270
#Mann= 10 ,-1 , 0
       0     .12       0     332    .045       0   360.7     .12       0
   546.6    .016       0  597.48     .12       0  686.24    .016       0
  744.16     .12       0  794.31    .016       0  827.88     .12       0
  830.46    .016       0
Bank Sta=332,360.7
XS Rating Curve= 0 ,0
Exp/Cntr=0.3,0.1

Type RM Length L Ch R = 1 ,18938.4 ,377.7,416.6,455.4
XS GIS Cut Line= 4
     1799165.139      258745.324       1799558.5      258929.615
     1799647.855       258879.63     1799929.799      258927.742
#Sta/Elev= 30
       0    1270   125.5 1230.14   144.8 1223.16   173.8 1211.66   193.1 1205.09
     251 1187.46   308.9 1172.04   318.6 1169.78   337.9 1167.21   434.4 1160.06
   443.7 1158.38     453 1155.04   462.3  1153.5   473.7 1154.62   490.2 1158.39
   499.6 1159.35   518.2 1159.64   527.5 1160.51   536.8 1162.01   574.9 1172.67
     613 1182.56   679.8 1198.64   708.4 1204.97  725.481208.075   756.1 1211.43
   765.6 1213.76  772.471217.101   784.7 1224.25   794.2 1229.17   822.8    1240
#Mann= 5 ,-1 , 0
       0     .12       0     453    .045       0   473.7     .12       0
  725.48    .016       0  772.47     .12       0
Bank Sta=453,473.7
XS Rating Curve= 0 ,0
Exp/Cntr=0.3,0.1

Type RM Length L Ch R = 1 ,18521.9 ,260.8,245.6,230.4
XS GIS Cut Line= 4
     1799047.407      258784.694     1799385.483      258968.725
     1799479.417      259190.558     1799808.282      259430.893
#Sta/Elev= 30
       0    1290   105.8 1258.28   182.8 1232.33   192.5 1228.13   202.1 1222.08
   221.3 1206.08     231 1200.02   240.6 1196.66   279.1 1188.64   336.8 1180.11
   375.3 1171.73   404.2 1167.04   433.1  1161.2   442.7 1159.61   490.9 1154.67
   510.2 1151.18   519.8 1150.24  531.26 1151.17   558.4 1158.03   606.6 1166.45
     684  1174.7   732.5 1181.06   771.3 1184.91   800.4 1189.06   819.8 1192.48
  859.131201.989   887.7  1204.4  903.621208.471   984.6 1230.08  1033.1    1240
#Mann= 5 ,-1 , 0
       0     .12       0   510.2    .045       0  531.26     .12       0
  859.13    .016       0  903.62     .12       0
Bank Sta=510.2,531.26
XS Rating Curve= 0 ,0
Exp/Cntr=0.3,0.1

Type RM Length L Ch R = 1 ,18276.2 ,260.3,252.9,245.2
XS GIS Cut Line= 2
     1798924.042      259068.708     1799773.688      259534.308
#Sta/Elev= 30
       0 1260.01    88.1 1225.47     137 1205.02   146.8 1201.96   166.4 1197.99
   195.7 1192.81   244.7 1186.77   254.4 1185.18   264.2 1182.99   293.6 1175.04
   313.2  1168.8   332.7 1161.02   362.1 1147.58  370.32 1145.68   371.8 1145.31
   381.7 1145.22   386.8 1145.63   518.7 1161.42   587.2 1166.92   616.5 1170.32
   694.8  1181.7   714.4 1185.67   773.1 1199.05   782.9 1200.81  789.091201.347
   812.3 1202.86  827.041205.833   841.6 1209.88   910.1 1230.78   968.9 1245.36
#Mann= 5 ,-1 , 0
       0     .12       0  370.32    .045       0   386.8     .12       0
  789.09    .016       0  827.04     .12       0
Bank Sta=370.32,386.8
XS Rating Curve= 0 ,0
Exp/Cntr=0.3,0.1

Type RM Length L Ch R = 1 ,18023.4 ,398.4,402.8,407.1
XS GIS Cut Line= 2
     1798822.201      259419.222     1799703.127      259562.548
#Sta/Elev= 30
       0    1260    78.5 1226.75   127.5 1208.02   166.7 1193.86   176.5 1191.29
   186.4 1189.39   225.6 1182.84   284.4 1170.13     304 1165.04   362.9  1147.2
   372.7  1145.2  406.71  1141.4   421.7 1140.43   431.5 1140.74  434.83 1141.32
     438 1141.76     461 1147.18   470.8 1148.34   500.2  1148.6     510 1149.35
   549.2    1155   578.7 1160.65   637.5 1173.58   686.6 1183.32   745.4  1196.1
  764.631199.096   784.6 1200.47   794.4 1202.39  804.511205.118   892.5    1230
#Mann= 6 ,-1 , 0
       0     .12       0  406.71    .045       0  434.83    .045       0
     438     .12       0  764.63    .016       0  804.51     .12       0
Bank Sta=406.71,434.83
XS Rating Curve= 0 ,0
Exp/Cntr=0.3,0.1

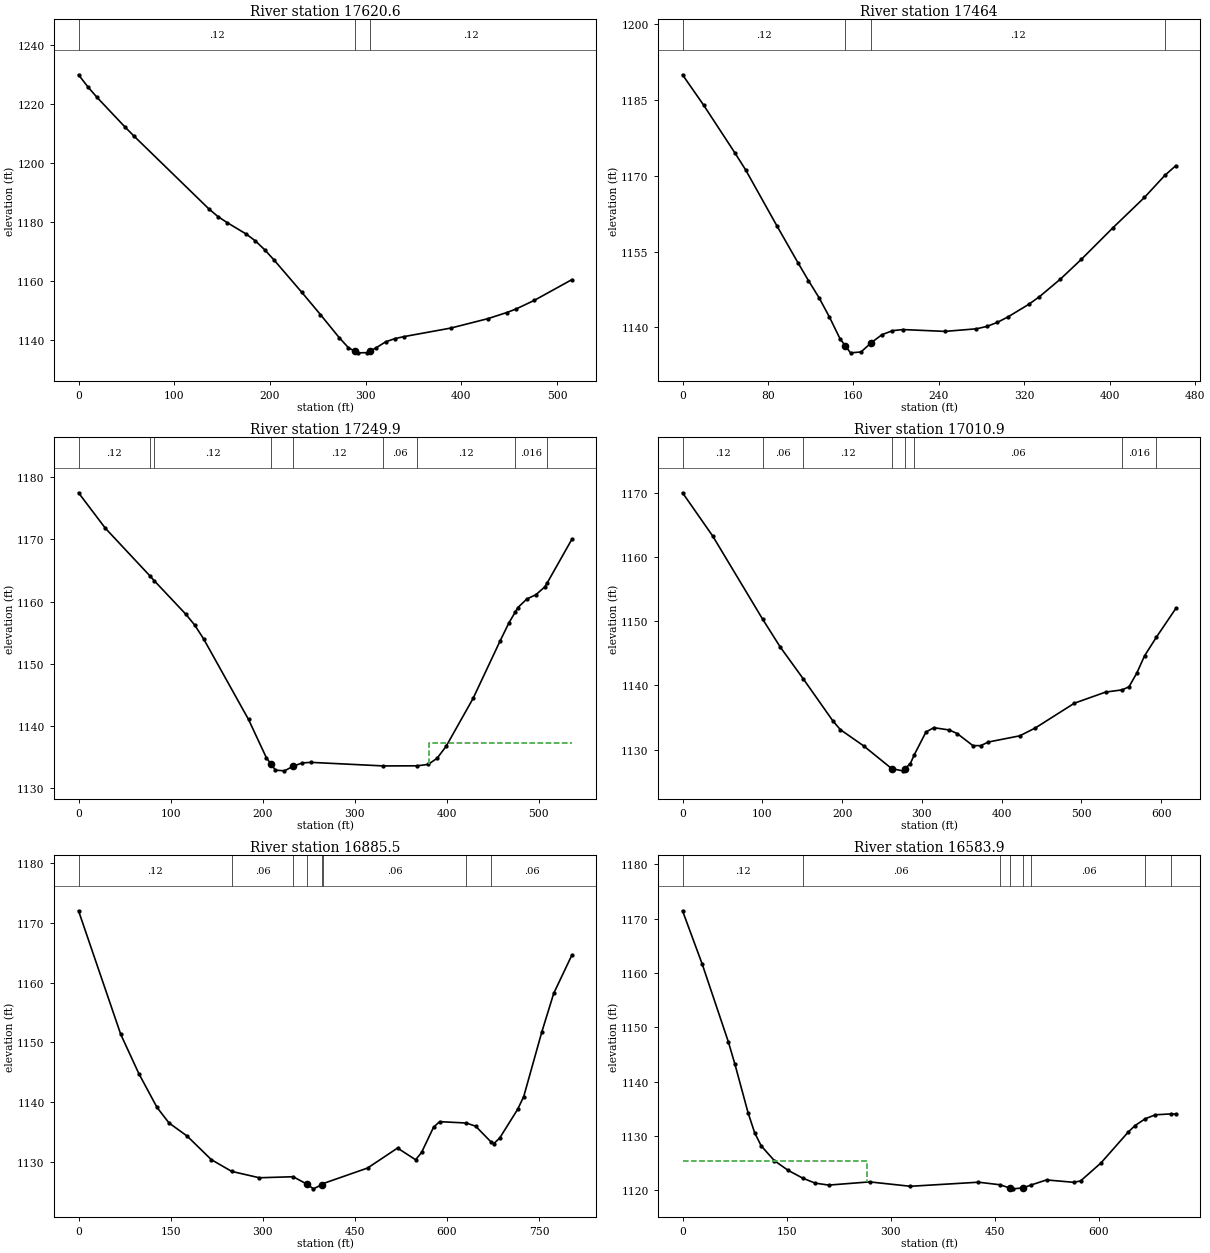
Type RM Length L Ch R = 1 ,17620.6 ,164.7,156.6,148.1
XS GIS Cut Line= 2
     1798939.533      259755.275     1799421.888      259936.708
#Sta/Elev= 30
       0 1230.01     9.7 1225.94    19.4 1222.31    48.6 1212.26    58.3 1209.08
   136.1 1184.48   145.8 1181.81   155.6 1179.73     175 1175.95   184.8 1173.57
   194.5 1170.57   204.2 1167.12   233.4 1156.07   252.8 1148.53   272.3 1140.74
     282 1137.29   289.1 1136.02   291.7 1135.55   301.4 1135.61   304.1 1136.08
   311.2 1137.31   320.9 1139.29   330.6 1140.39   340.3 1141.08   388.9 1143.96
   427.8 1147.17   447.3 1149.23     457 1150.42   476.4 1153.41   515.4 1160.41
#Mann= 3 ,-1 , 0
       0     .12       0   289.1    .045       0   304.1     .12       0
Bank Sta=289.1,304.1
XS Rating Curve= 0 ,0
Exp/Cntr=0.3,0.1

Type RM Length L Ch R = 1 ,17464   ,213.2,214.1,214.9
XS GIS Cut Line= 2
     1799014.445      260009.211     1799476.375      260005.835
#Sta/Elev= 30
       0    1190    19.7 1184.01    49.1 1174.51      59  1171.2    88.5 1160.03
   108.1 1152.77   117.9 1149.24   127.8 1145.86   137.6    1142   147.4 1137.75
   152.3 1136.35   157.3 1134.93   167.1  1135.1   176.9 1136.97   186.7 1138.52
   196.6 1139.32   206.4 1139.54   245.7 1139.18   275.2 1139.69     285 1140.16
   294.9 1140.98   304.7 1142.04   324.3 1144.55   334.2 1146.05   353.8 1149.53
   373.5 1153.46     403  1159.7   432.5  1165.7  451.671170.091   461.9    1172
#Mann= 4 ,-1 , 0
       0     .12       0   152.3    .045       0   176.9     .12       0
  451.67    .016       0
Bank Sta=152.3,176.9
XS Rating Curve= 0 ,0
Exp/Cntr=0.3,0.1

Type RM Length L Ch R = 1 ,17249.9 ,236.2,239,241.5
XS GIS Cut Line= 3
     1798980.459      260139.777     1799090.744      260219.261
     1799490.602      260231.545
#Sta/Elev= 30
       0 1177.49    29.1  1171.8   77.341164.167   82.49 1163.32   116.5 1157.98
   126.2 1156.23   135.9 1154.01   184.7 1141.05   204.2 1134.87   208.9 1133.93
     214  1132.9   223.8 1132.79   233.5 1133.55   243.3 1134.07     253 1134.15
  331.361133.579  367.721133.598   379.9 1133.82   389.6 1134.81   399.4 1136.73
   428.7 1144.43   457.9 1153.62   467.7 1156.59  474.271158.249   477.4 1159.04
   487.2 1160.42     497 1161.11   506.7 1162.37  509.17 1162.98     536    1170
#Mann= 9 ,-1 , 0
       0     .12       0   77.34     .06       0   82.49     .12       0
   208.9    .045       0   233.5     .12       0  331.36     .06       0
  367.72     .12       0  474.27    .016       0  509.17     .12       0
#XS Ineff= 2 , 0
                          380.55         1137.19
Permanent Ineff=
       F       F
Bank Sta=208.9,233.5
XS Rating Curve= 0 ,0
Exp/Cntr=0.3,0.1

Type RM Length L Ch R = 1 ,17010.9 ,116.5,125.4,134.3
XS GIS Cut Line= 3
     1798931.633      260255.301     1799038.649      260432.914
     1799445.006      260494.783
#Sta/Elev= 30
       0    1170    37.7 1163.29  100.321150.342   122.5 1145.98  151.431141.014
   188.5 1134.47   197.9 1133.11   226.9  1130.6  262.14 1127.05   275.9  1126.7
   278.9 1127.05   285.6 1127.83  290.691129.243   305.2 1132.75     315 1133.42
   334.6 1133.06   344.4  1132.5     364 1130.63   373.7 1130.62   383.5 1131.19
   422.7 1132.15   442.2 1133.37   491.2 1137.23   530.3 1138.96  551.171139.311
   559.7 1139.79   569.5 1141.93   579.2 1144.61  593.981147.504   618.4 1151.99
#Mann= 8 ,-1 , 0
       0     .12       0  100.32     .06       0  151.43     .12       0
  262.14    .045       0   278.9     .12       0  290.69     .06       0
  551.17    .016       0  593.98     .12       0
Bank Sta=262.14,278.9
XS Rating Curve= 0 ,0
Exp/Cntr=0.3,0.1

Type RM Length L Ch R = 1 ,16885.5 ,292.3,301.6,310.3
XS GIS Cut Line= 3
     1798823.338       260298.17     1798923.604      260467.258
     1799443.243      260780.415
#Sta/Elev= 30
       0 1171.99    68.8 1151.34    98.3 1144.78   127.8 1139.15   147.4 1136.55
   176.9 1134.36   216.2 1130.43   249.41128.465   294.4  1127.4  349.551127.572
   372.7 1126.29   382.5 1125.55   396.3 1126.25  398.131126.426   470.6 1129.02
   519.5 1132.36   548.9 1130.41   558.6 1131.62   578.2 1135.85     588 1136.77
  631.461136.543   646.7 1136.01  671.781133.376   676.1 1133.09   685.9 1134.04
   715.2 1138.85     725 1140.97   754.4 1151.74   773.9 1158.22   803.3 1164.57
#Mann= 8 ,-1 , 0
       0     .12       0   249.4     .06       0  349.55     .12       0
   372.7    .045       0   396.3     .12       0  398.13     .06       0
  631.46    .016       0  671.78     .06       0
Bank Sta=372.7,396.3
XS Rating Curve= 0 ,0
Exp/Cntr=0.3,0.1

Type RM Length L Ch R = 1 ,16583.9 ,191.7,194.7,197.4
XS GIS Cut Line= 3
     1798674.289       260363.41      1798676.58      260495.747
     1799017.992      260963.438
#Sta/Elev= 30
       0 1171.43    28.4 1161.61    66.2 1147.26    75.6 1143.17    94.5 1134.26
     104 1130.58   113.4 1128.17   132.4 1125.44     152 1123.68  173.181122.228
   191.2  1121.3   210.9 1120.94   269.8 1121.53   328.6 1120.72   426.8 1121.47
  457.921120.999   471.8  1120.4   475.9 1120.25  490.48 1120.41  503.221120.978
   524.9 1121.89   564.2 1121.45     574  1121.7   603.4 1125.01   642.7 1130.69
   652.5 1131.89  667.351133.152     682 1133.88  704.941134.046   711.4    1134
#Mann= 8 ,-1 , 0
       0     .12       0  173.18     .06       0  457.92     .12       0
   471.8    .045       0  490.48     .12       0  503.22     .06       0
  667.35    .016       0  704.94     .06       0
#XS Ineff= 2 , 0
          266.37  1125.4
Permanent Ineff=
       F       F
Bank Sta=471.8,490.48
XS Rating Curve= 0 ,0
Exp/Cntr=0.3,0.1

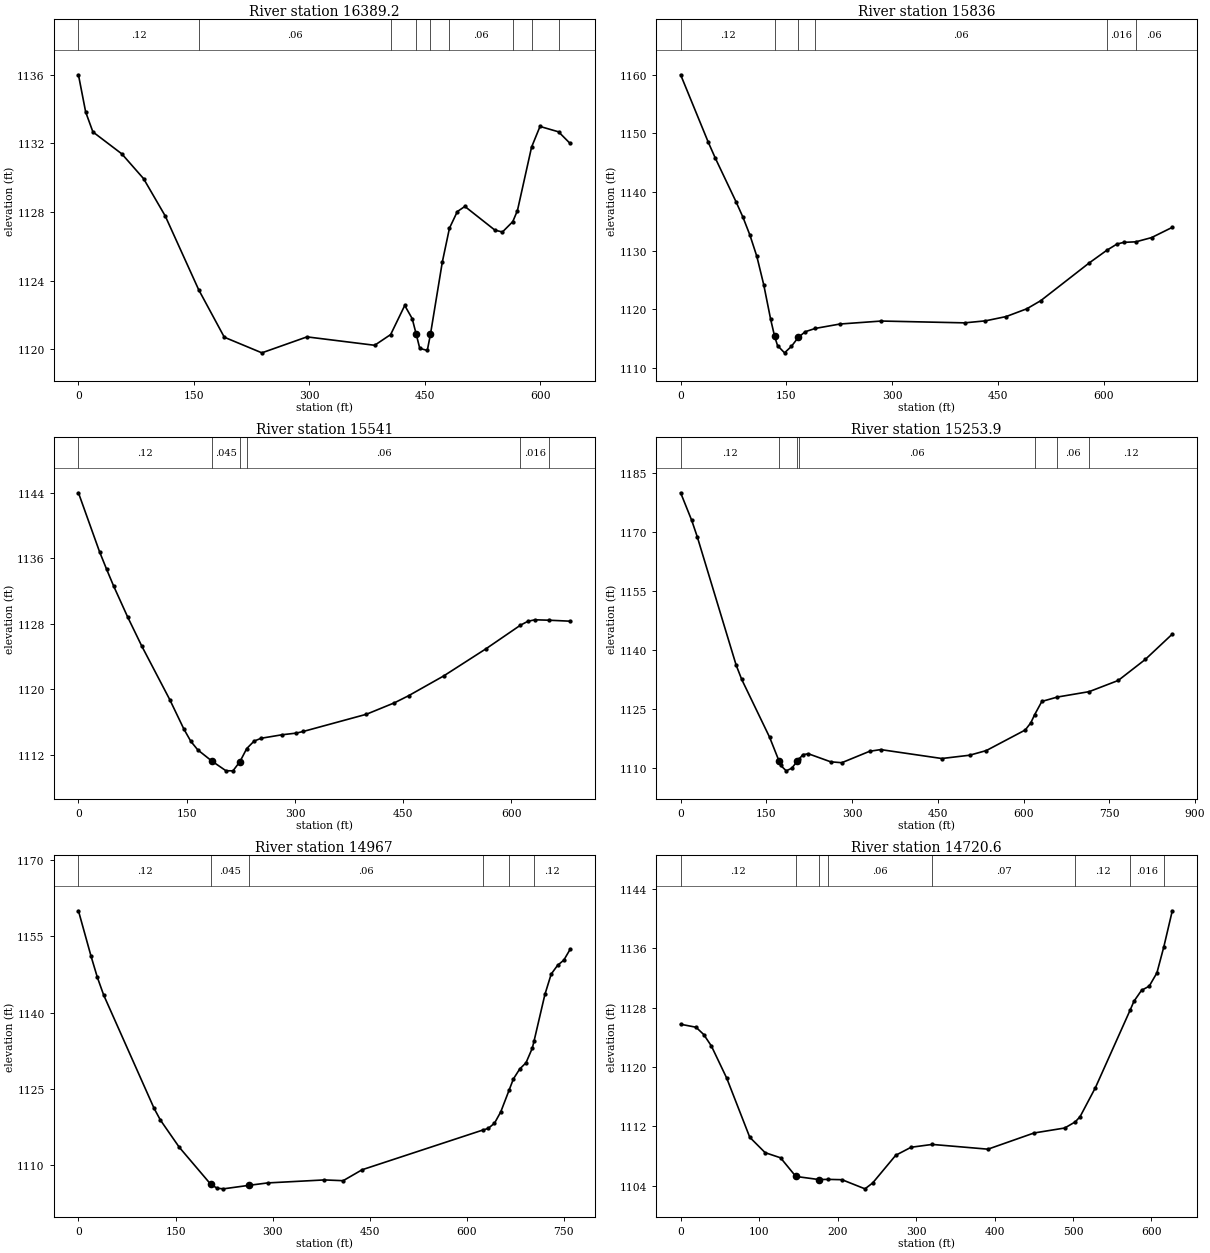
Type RM Length L Ch R = 1 ,16389.2 ,549,553.3,554.7
XS GIS Cut Line= 3
     1798460.735      260576.033     1798601.059      260630.322
     1798835.954      261058.316
#Sta/Elev= 30
       0    1136     9.4 1133.83    18.8 1132.67    56.4 1131.39    84.6 1129.95
   112.8 1127.77   156.21123.477   189.5 1120.71   238.3  1119.8   296.9 1120.73
   384.8 1120.24   405.61120.866   423.9 1122.56   433.6 1121.79  438.65 1120.91
   443.4 1120.06   453.2 1119.94  457.34 1120.89   472.7 1125.09     4821127.065
   492.2 1128.03     502 1128.33     541 1126.95   550.8 1126.84  564.211127.443
   570.3 1128.09  588.631131.782   599.6 1132.99  623.721132.676   638.7    1132
#Mann= 9 ,-1 , 0
       0     .12       0   156.2     .06       0   405.6     .12       0
  438.65    .045       0  457.34     .12       0     482     .06       0
  564.21     .08       0  588.63    .016       0  623.72     .06       0
Bank Sta=438.65,457.34
XS Rating Curve= 0 ,0
Exp/Cntr=0.3,0.1

Type RM Length L Ch R = 1 ,15836   ,295.9,294.9,294.5
XS GIS Cut Line= 2
     1798167.988      260614.714     1798461.821      261246.767
#Sta/Elev= 30
       0    1160    39.3 1148.47    49.1 1145.81    78.5 1138.37    88.4 1135.71
    98.2 1132.68     108 1129.06   117.8 1124.22   127.6 1118.33  133.24 1115.41
   137.4 1113.84   147.3 1112.61   157.1 1113.72   166.9 1115.26   176.7 1116.21
  190.871116.771   225.8 1117.52   284.7 1118.03   402.5 1117.72     432 1118.06
   461.4 1118.79   490.8 1120.12   510.5  1121.5   579.2 1127.93  603.871130.065
   618.5 1131.15   628.3 1131.44  645.391131.532   667.6 1132.25     697    1134
#Mann= 6 ,-1 , 0
       0     .12       0  133.24    .045       0   166.9     .12       0
  190.87     .06       0  603.87    .016       0  645.39     .06       0
Bank Sta=133.24,166.9
XS Rating Curve= 0 ,0
Exp/Cntr=0.3,0.1

Type RM Length L Ch R = 1 ,15541   ,284.7,287.1,286.8
XS GIS Cut Line= 2
     1797937.839      260726.743     1798256.205      261328.926
#Sta/Elev= 30
       0 1143.98    29.2  1136.8    38.9 1134.68    48.6 1132.64    68.1 1128.85
    87.6 1125.31   126.5 1118.76     146 1115.18   155.7 1113.67   165.4 1112.62
   184.9 1111.26   204.4 1110.08   214.1 1110.07   223.8  1111.2   233.21112.789
   243.3 1113.69     253 1114.04   282.2 1114.47   301.7 1114.67   311.4 1114.87
     399 1116.97   437.9 1118.37   457.4 1119.23     506 1121.64   564.4 1124.94
   612.41127.832   622.8 1128.31   632.5 1128.49  651.99 1128.44   681.2 1128.32
#Mann= 6 ,-1 , 0
       0     .12       0   184.9    .045       0   223.8     .12       0
   233.2     .06       0   612.4    .016       0  651.99     .06       0
Bank Sta=184.9,223.8
XS Rating Curve= 0 ,0
Exp/Cntr=0.3,0.1

Type RM Length L Ch R = 1 ,15253.9 ,284.3,286.9,288.5
XS GIS Cut Line= 3
     1797721.916      260831.938     1798008.227      261438.601
     1797964.745      261622.789
#Sta/Elev= 30
       0    1180    19.4 1172.96    29.2 1168.74    97.2 1136.06   106.9 1132.44
   155.6 1117.74  172.39 1111.58     175 1110.56   184.7 1109.17   194.4 1109.84
   204.2 1111.66  206.951112.122   213.9  1113.3   223.6 1113.51   262.5 1111.47
   281.9 1111.24   330.6 1114.15     350 1114.58   456.9 1112.31   505.6 1113.15
   534.7 1114.33   602.8 1119.57   612.5 1121.38   619.4  1123.5   631.9 1126.85
  659.091127.969  714.671129.343   765.5 1132.19   812.8 1137.54   860.1    1144
#Mann= 7 ,-1 , 0
       0     .12       0  172.39    .045       0   204.2     .12       0
  206.95     .06       0   619.4    .016       0  659.09     .06       0
  714.67     .12       0
Bank Sta=172.39,204.2
XS Rating Curve= 0 ,0
Exp/Cntr=0.3,0.1

Type RM Length L Ch R = 1 ,14967   ,247.1,246.4,244.9
XS GIS Cut Line= 2
     1797469.169      260914.111     1797755.511      261617.728
#Sta/Elev= 30
       0    1160    19.5 1151.07    29.2 1146.94      39 1143.45   116.9  1121.2
   126.6 1118.91   155.8 1113.56   204.5 1106.28   214.3 1105.52     224  1105.4
     263 1106.08   292.2 1106.56   379.8 1107.15     409    1107   438.3 1109.15
  624.62 1116.94     633 1117.26   642.8 1118.29   652.5 1120.52  665.681124.882
     672 1126.98   681.7 1128.92   691.5 1130.16   701.2 1133.02  704.011134.477
   720.7 1143.58   730.4 1147.57   740.2 1149.28   749.9 1150.31   759.6 1152.42
#Mann= 6 ,-1 , 0
       0     .12       0   204.5    .045       0     263     .06       0
  624.62     .12       0  665.68    .016       0  704.01     .12       0
Bank Sta=204.5,263
XS Rating Curve= 0 ,0
Exp/Cntr=0.3,0.1

Type RM Length L Ch R = 1 ,14720.6 ,276.7,278.9,280.8
XS GIS Cut Line= 2
     1797274.111      261097.433     1797537.462      261665.896
#Sta/Elev= 30
       0 1125.76    19.6 1125.36    29.4 1124.38    39.2 1122.83    58.7 1118.51
    88.1 1110.54   107.7 1108.47   127.3 1107.78   146.8 1105.27   176.2 1104.85
  187.561104.875   205.6 1104.83   234.9  1103.6   244.7 1104.39   274.1 1108.12
   293.7  1109.2  320.59 1109.58   391.6 1108.94   450.3 1111.12   489.4 1111.79
  502.821112.614     509 1113.32   528.6 1117.24  573.011127.721   577.6 1128.85
   587.3 1130.33   597.1 1130.89   606.9 1132.68  615.631136.154   626.5 1141.04
#Mann= 8 ,-1 , 0
       0     .12       0   146.8    .045       0   176.2     .12       0
  187.56     .06       0  320.59     .07       0  502.82     .12       0
  573.01    .016       0  615.63     .12       0
Bank Sta=146.8,176.2
XS Rating Curve= 0 ,0
Exp/Cntr=0.3,0.1

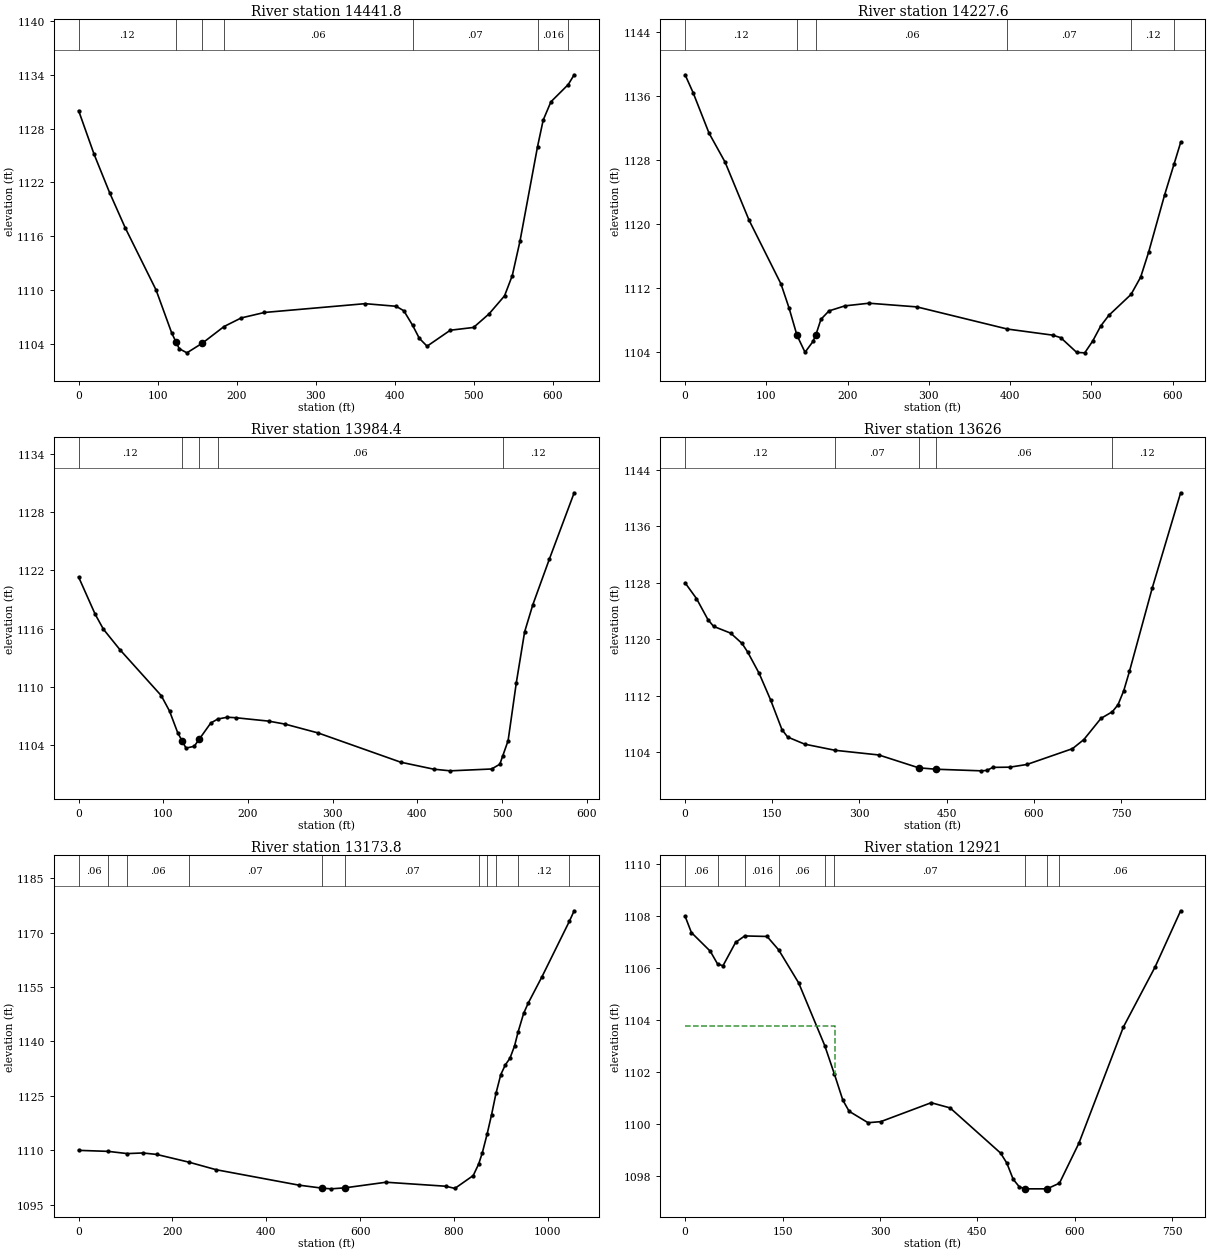
Type RM Length L Ch R = 1 ,14441.8 ,215.9,214.2,212.2
XS GIS Cut Line= 2
     1797036.098      261208.969     1797245.987      261799.701
#Sta/Elev= 30
       0    1130    19.6 1125.13    39.2 1120.86    58.8 1116.97      98 1110.01
   117.6 1105.26   123.3 1104.19   127.3 1103.47     137 1103.01   156.7  1104.1
  184.011105.945   205.7  1106.9   235.1 1107.51   362.4 1108.49   401.6  1108.2
   411.4  1107.7  422.461106.085     431 1104.63   440.8 1103.75   470.2 1105.53
   499.6 1105.84   519.2 1107.35   538.8 1109.36   548.6 1111.62   558.3 1115.44
  580.511125.971   587.7 1128.95   597.5 1130.99  619.351132.906   626.9    1134
#Mann= 7 ,-1 , 0
       0     .12       0   123.3    .045       0   156.7     .12       0
  184.01     .06       0  422.46     .07       0  580.51    .016       0
  619.35     .12       0
Bank Sta=123.3,156.7
XS Rating Curve= 0 ,0
Exp/Cntr=0.3,0.1

Type RM Length L Ch R = 1 ,14227.6 ,239,243.2,247.2
XS GIS Cut Line= 2
     1796819.586      261273.129     1797070.426      261829.087
#Sta/Elev= 30
       0 1138.62     9.8  1136.4    29.5 1131.32    49.2 1127.71    78.7 1120.46
     118 1112.49   127.9  1109.5   137.7 1106.07   147.6 1103.95   157.4  1105.3
  161.08 1106.17   167.2 1108.07   177.1 1109.12   196.8 1109.75   226.3 1110.08
   285.3 1109.62  396.681106.852   452.5 1106.09   462.4 1105.77     482 1103.93
   491.9 1103.88   501.7 1105.36   511.6 1107.24   521.4 1108.55  548.821111.175
   560.7 1113.34   570.6 1116.49   590.2 1123.62  601.781127.459   609.9 1130.16
#Mann= 6 ,-1 , 0
       0     .12       0   137.7    .045       0  161.08     .06       0
  396.68     .07       0  548.82     .12       0  601.78     .06       0
Bank Sta=137.7,161.08
XS Rating Curve= 0 ,0
Exp/Cntr=0.3,0.1

Type RM Length L Ch R = 1 ,13984.4 ,370,358.4,346.6
XS GIS Cut Line= 2
     1796635.936      261383.715     1796774.255      261952.228
#Sta/Elev= 30
       0 1121.32    19.5  1117.5    29.2 1115.96    48.8 1113.84    97.5 1109.12
   107.3 1107.53     117 1105.29   122.2 1104.45   126.8 1103.71   136.5  1103.9
  142.33 1104.62     156 1106.29  164.271106.703   175.5 1106.89   185.3 1106.84
   224.3 1106.49   243.8 1106.18   282.8 1105.27   380.3 1102.26   419.3 1101.54
   438.8 1101.37   487.6 1101.56   497.3 1102.05  500.621102.873   507.1 1104.48
   516.8 1110.45   526.6 1115.68   536.3 1118.48   555.8 1123.17   585.1    1130
#Mann= 5 ,-1 , 0
       0     .12       0   122.2    .045       0  142.33     .12       0
  164.27     .06       0  500.62     .12       0
Bank Sta=122.2,142.33
XS Rating Curve= 0 ,0
Exp/Cntr=0.3,0.1

Type RM Length L Ch R = 1 ,13626   ,456.4,452.2,447.5
XS GIS Cut Line= 2
     1796120.744      261428.424      1796701.04      262052.986
#Sta/Elev= 30
       0    1128    19.6 1125.77    39.2  1122.8      49 1121.83    78.4 1120.87
      98 1119.41   107.8 1118.17   127.4 1115.17     147 1111.43   166.6 1107.21
   176.4 1106.15   205.8 1105.14  258.09 1104.27   333.2 1103.61   401.8 1101.79
   431.2 1101.59   509.6 1101.36   519.4 1101.42   529.2 1101.85   558.6 1101.88
     588 1102.26   666.4  1104.5     686 1105.79   715.4 1108.79  735.041109.734
   744.8 1110.73   754.6 1112.71   764.4 1115.44   803.5 1127.22   852.5 1140.76
#Mann= 5 ,-1 , 0
       0     .12       0  258.09     .07       0   401.8    .045       0
   431.2     .06       0  735.04     .12       0
Bank Sta=401.8,431.2
XS Rating Curve= 0 ,0
Exp/Cntr=0.3,0.1

Type RM Length L Ch R = 1 ,13173.8 ,249,252.8,255.9
XS GIS Cut Line= 2
     1795671.593      261759.995     1796530.816      262373.901
#Sta/Elev= 30
       0    1110   63.031109.721  103.581109.111   136.9 1109.28   166.2 1108.88
  234.851106.754   293.3 1104.66   469.3 1100.42   518.2  1099.6   537.8  1099.4
   567.1 1099.67   655.1 1101.22   782.2 1100.12   801.8 1099.52   840.9 1103.06
  852.611106.274   860.4 1109.39  870.391114.437     880 1119.83  889.351125.698
   899.6 1130.87   909.3 1133.55   919.1 1135.36   928.9 1138.74  936.611142.658
   948.4 1147.77   958.2  1150.6   987.6 1157.88 1045.821173.127    1056    1176
#Mann= 11 ,-1 , 0
       0     .06       0   63.03    .016       0  103.58     .06       0
  234.85     .07       0   518.2    .045       0   567.1     .07       0
  852.61     .12       0  870.39     .06       0  889.35    .016       0
  936.61     .12       0 1045.82     .06       0
Bank Sta=518.2,567.1
XS Rating Curve= 0 ,0
Exp/Cntr=0.3,0.1

Type RM Length L Ch R = 1 ,12921   ,131.2,134.9,138.3
XS GIS Cut Line= 4
       1795620.8       261877.27     1795963.617      262274.136
     1795974.804      262281.194     1796119.009      262454.028
#Sta/Elev= 30
       0    1108     9.7 1107.37    38.8 1106.65      501106.158    58.3 1106.09
    77.7 1106.99   91.73 1107.24   126.2 1107.22  144.011106.703   174.8 1105.43
  214.971103.012  229.961101.903   242.8 1100.91   252.5 1100.48   281.6 1100.04
   301.1 1100.08   378.8 1100.81   407.9 1100.61   485.6 1098.87   495.3 1098.48
     505 1097.86   514.7 1097.56   522.9  1097.5   524.4 1097.49   557.2 1097.49
  576.271097.709   606.2 1099.25   674.7 1103.73   723.6 1106.05   762.8 1108.21
#Mann= 9 ,-1 , 0
       0     .06       0      50     .12       0   91.73    .016       0
  144.01     .06       0  214.97     .12       0  229.96     .07       0
   522.9    .045       0   557.2     .07       0  576.27     .06       0
#XS Ineff= 2 , 0
          230.19 1103.75
Permanent Ineff=
       F       F
Bank Sta=522.9,557.2
XS Rating Curve= 0 ,0
Exp/Cntr=0.3,0.1

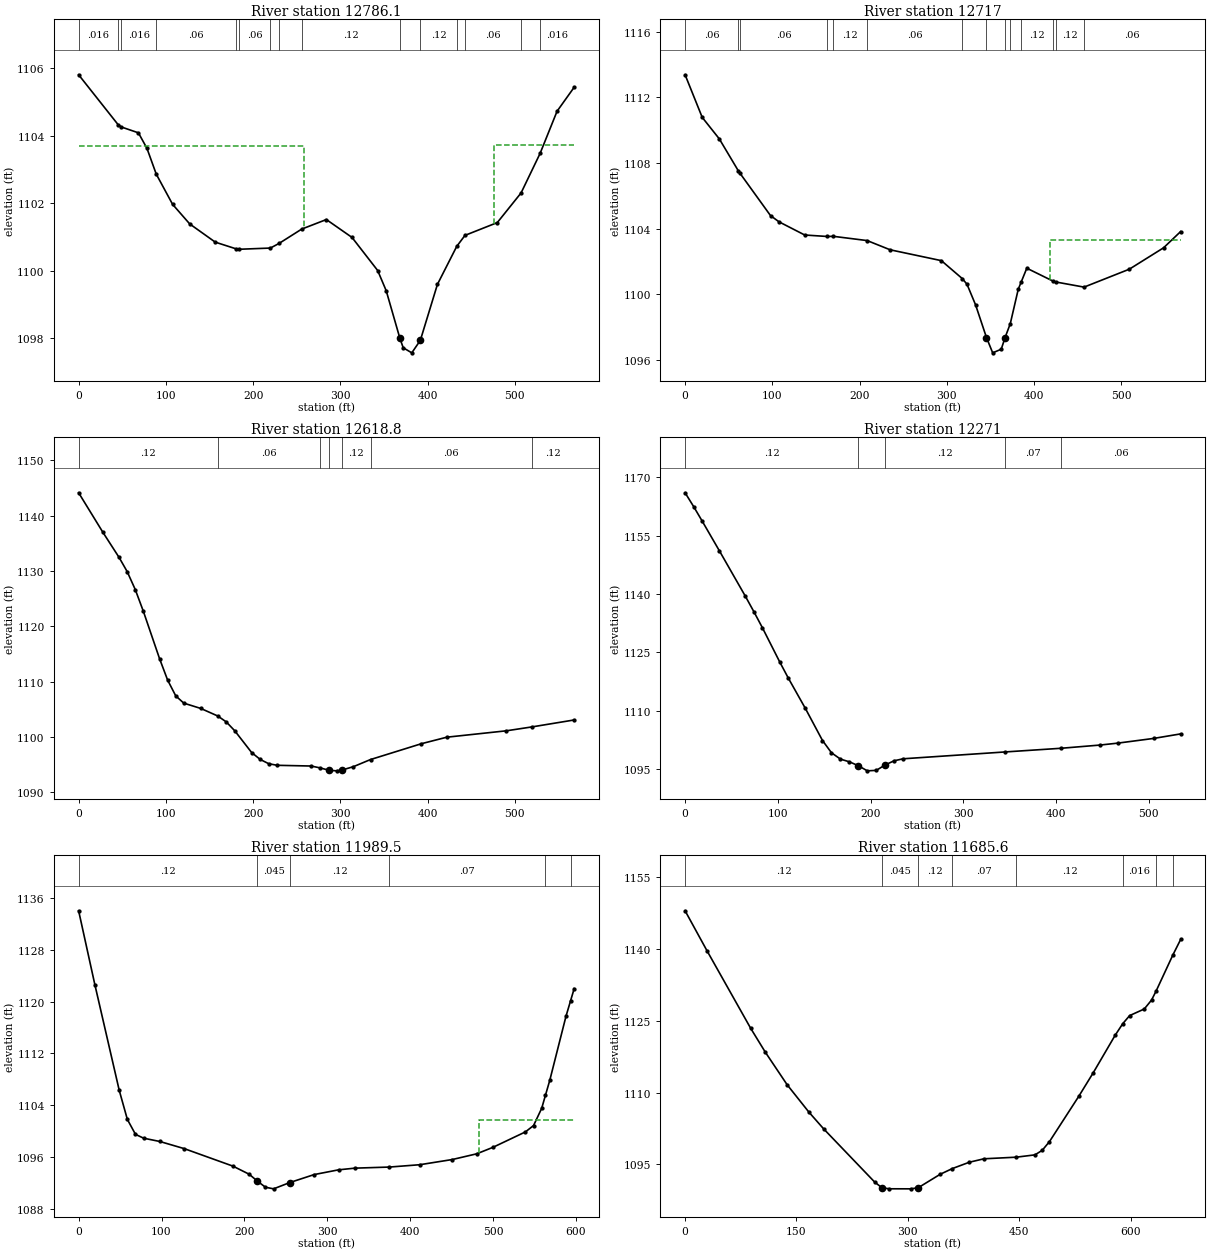
Type RM Length L Ch R = 1 ,12786.1 ,69.3,69.1,69.7
XS GIS Cut Line= 2
     1795640.199      262038.487     1795971.025       262500.03
#Sta/Elev= 30
       0  1105.8   45.141104.325   48.811104.254    68.5 1104.08    78.3 1103.62
   88.971102.855   107.7 1101.96   127.3 1101.38   156.6 1100.84   180.31100.643
  183.811100.629  219.731100.665  229.691100.802  255.641101.227   283.9 1101.51
   313.3 1100.98   342.7    1100   352.5  1099.4  368.18 1097.99     372 1097.71
   381.8 1097.56   391.6 1097.93   411.2 1099.59  433.321100.715  442.771101.041
   479.8 1101.42  507.061102.299  528.85 1103.47   548.3 1104.72   567.9 1105.43
#Mann= 15 ,-1 , 0
       0    .016       0   45.14     .06       0   48.81    .016       0
   88.97     .06       0   180.3     .07       0  183.81     .06       0
  219.73    .016       0  229.69     .06       0  255.64     .12       0
  368.18    .045       0   391.6     .12       0  433.32    .016       0
  442.77     .06       0  507.06     .08       0  528.85    .016       0
#XS Ineff= 2 , 0
          257.77 1103.68   476.2         1103.72
Permanent Ineff=
       F       F
Bank Sta=368.18,391.6
XS Rating Curve= 0 ,0
Exp/Cntr=0.3,0.1

Type RM Length L Ch R = 1 ,12717   ,468.6,446,423
XS GIS Cut Line= 2
     1795589.068      262080.335     1795919.895      262541.877
#Sta/Elev= 30
       0 1113.37    19.6 1110.78    39.2 1109.47   60.84 1107.54   62.621107.398
    97.9  1104.8   107.7 1104.42   137.1 1103.62  163.04 1103.53  169.88 1103.54
  208.651103.281     235 1102.72   293.7 1102.06  317.711100.966   323.1 1100.62
   332.9 1099.37  345.39 1097.38   352.5 1096.45   362.3 1096.67   366.7 1097.38
  372.671098.224   381.8 1100.32  385.381100.787   391.6  1101.6   421.31100.824
  424.581100.764  457.221100.449   509.1 1101.54   548.3 1102.84   567.9 1103.83
#Mann= 14 ,-1 , 0
       0     .06       0   60.84    .016       0   62.62     .06       0
  163.04    .016       0  169.88     .12       0  208.65     .06       0
  317.71     .12       0  345.39    .045       0   366.7     .12       0
  372.67    .016       0  385.38     .12       0   421.3     .06       0
  424.58     .12       0  457.22     .06       0
#XS Ineff= 2 , 0
                           418.2         1103.29
Permanent Ineff=
       F       F
Bank Sta=345.39,366.7
XS Rating Curve= 0 ,0
Exp/Cntr=0.3,0.1

Type RM Length L Ch R = 1 ,12618.8 ,369.6,347.9,325.5
XS GIS Cut Line= 3
     1795481.845      262237.579     1795599.032      262265.791
     1795870.849      262621.129
#Sta/Elev= 30
       0 1144.12    27.8 1136.98    46.4 1132.43    55.6 1129.89    64.9 1126.64
    74.2  1122.7    92.7 1114.17     102 1110.28   111.3 1107.43   120.5 1106.12
     140 1105.16   159.4  1103.8   169.2 1102.73   178.9 1101.13   198.3 1097.19
   208.1 1095.95   217.8 1095.18   227.5 1094.89   266.4 1094.76   276.2 1094.44
   287.2 1093.99   295.6 1093.89   302.2 1094.05     315 1094.65   334.5 1095.93
   392.8 1098.79     422 1099.97   490.1 1101.12   519.3 1101.82   567.9 1103.08
#Mann= 7 ,-1 , 0
       0     .12       0   159.4     .06       0   276.2     .12       0
   287.2    .045       0   302.2     .12       0   334.5     .06       0
   519.3     .12       0
Bank Sta=287.2,302.2
XS Rating Curve= 0 ,0
Exp/Cntr=0.3,0.1

Type RM Length L Ch R = 1 ,12271   ,275.6,281.5,287.4
XS GIS Cut Line= 3
     1795360.299      262642.962     1795506.854      262665.318
     1795892.313      262640.909
#Sta/Elev= 26
       0    1166     9.3 1162.42    18.5 1158.69    37.1 1151.03    64.9 1139.44
    74.1 1135.46    83.4 1131.29   101.9 1122.58   111.2  1118.4   129.7 1110.56
   148.2  1102.3   157.9 1099.14   167.6 1097.51   177.2 1096.82   186.9 1095.82
   196.5  1094.5   206.2 1094.62   215.8 1096.02   225.5 1097.09   235.2  1097.6
  345.211099.359  405.711100.306   447.6 1101.13   466.9 1101.63   505.5 1102.84
   534.5    1104
#Mann= 5 ,-1 , 0
       0     .12       0   186.9    .045       0   215.8     .12       0
  345.21     .07       0  405.71     .06       0
Bank Sta=186.9,215.8
XS Rating Curve= 0 ,0
Exp/Cntr=0.3,0.1

Type RM Length L Ch R = 1 ,11989.5 ,302.5,303.9,305.1
XS GIS Cut Line= 2
     1795353.027       262893.96       1795939.1      263012.304
#Sta/Elev= 30
       0    1134    19.6  1122.6      49 1106.31    58.8 1101.83    68.6 1099.53
    78.4 1098.94      98 1098.43   127.4 1097.33   186.2 1094.63   205.8 1093.38
   215.6 1092.33   225.4 1091.38   235.2 1091.13   254.8  1092.1   284.2 1093.33
   313.6 1094.06   333.3 1094.32  374.971094.488   411.7 1094.85   450.9 1095.65
   480.3 1096.53   499.9 1097.53   539.1 1099.91   548.9 1100.89   558.7 1103.54
  563.251105.555   568.5 1107.88   588.1 1117.77  593.491120.097   597.9    1122
#Mann= 6 ,-1 , 0
       0     .12       0   215.6    .045       0   254.8     .12       0
  374.97     .07       0  563.25     .06       0  593.49    .016       0
#XS Ineff= 2 , 0
                          482.65         1101.69
Permanent Ineff=
       F       F
Bank Sta=215.6,254.8
XS Rating Curve= 0 ,0
Exp/Cntr=0.3,0.1

Type RM Length L Ch R = 1 ,11685.6 ,305.1,312.9,320.3
XS GIS Cut Line= 2
     1795245.876      263165.465     1795891.294      263335.112
#Sta/Elev= 30
       0    1148    29.4 1139.67    88.3 1123.44     108 1118.45   137.4 1111.64
   166.8  1105.9   186.5 1102.43   255.2 1091.31     265 1090.11   274.8 1089.89
   304.2 1089.88     314 1090.12   343.5 1092.92  359.831094.116   382.7 1095.44
   402.4 1096.16  445.871096.496   471.1 1096.98   480.9 1097.93   490.7 1099.76
     530 1109.19   549.6 1114.14     579 1121.95  589.311124.393   598.6 1126.09
   618.3 1127.47   628.1 1129.33  634.331131.243  656.731138.725   667.3    1142
#Mann= 8 ,-1 , 0
       0     .12       0     265    .045       0     314     .12       0
  359.83     .07       0  445.87     .12       0  589.31    .016       0
  634.33     .12       0  656.73     .06       0
Bank Sta=265,314
XS Rating Curve= 0 ,0
Exp/Cntr=0.3,0.1