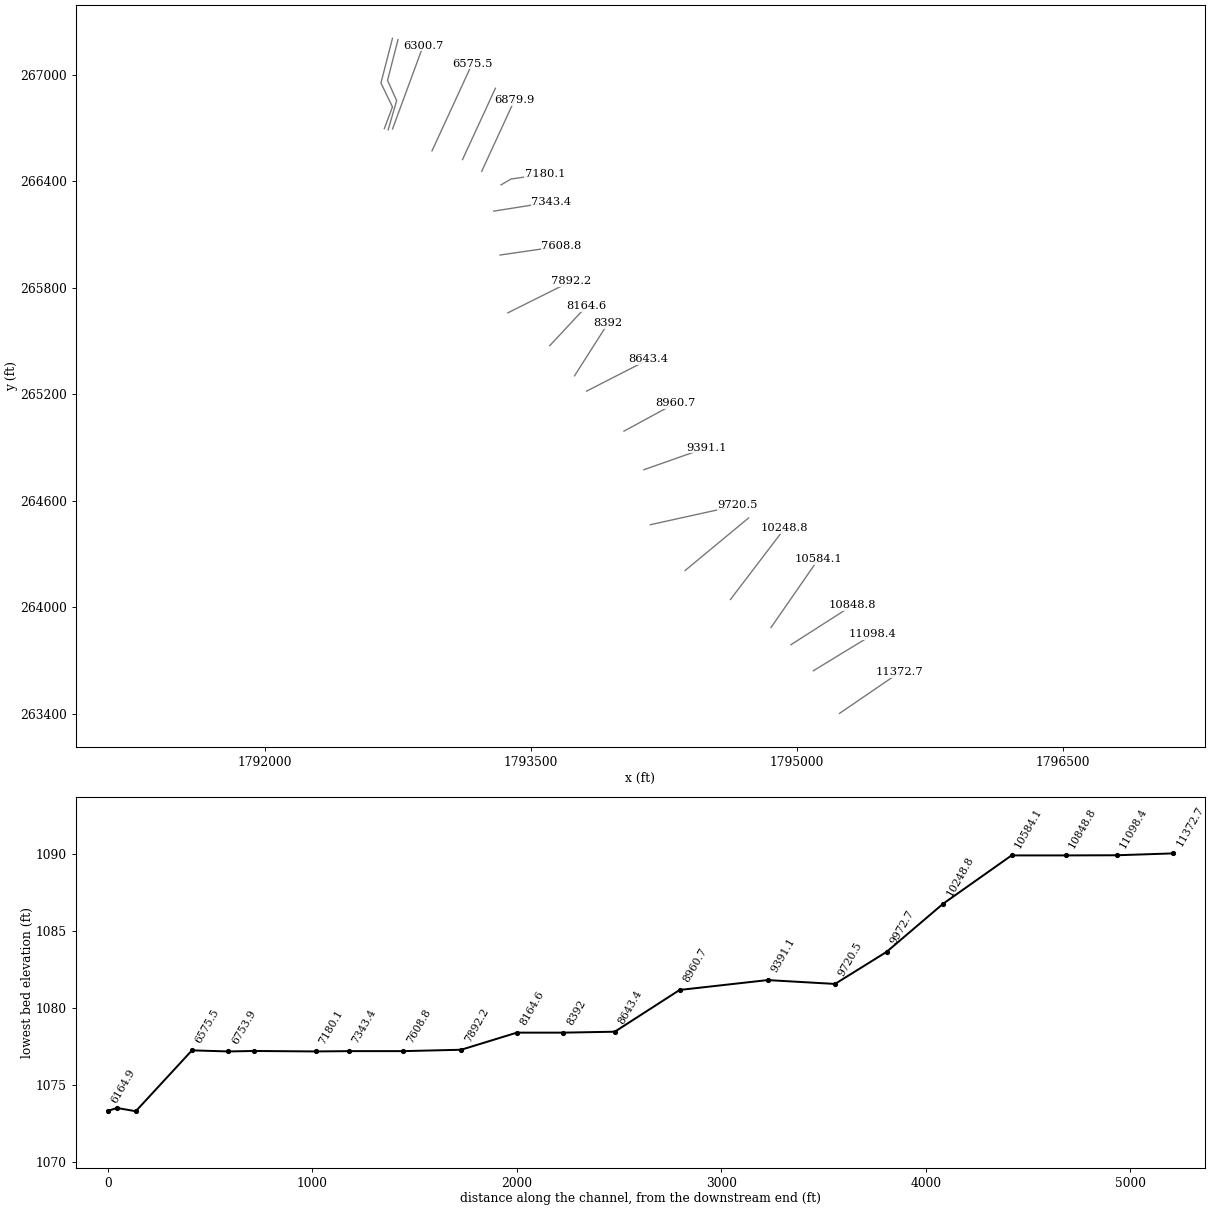
HEC-RAS study SIMPSONCK.prj: SIMPSONCK

--- SIMPSONCK.g01 (geometry) --- (continued)

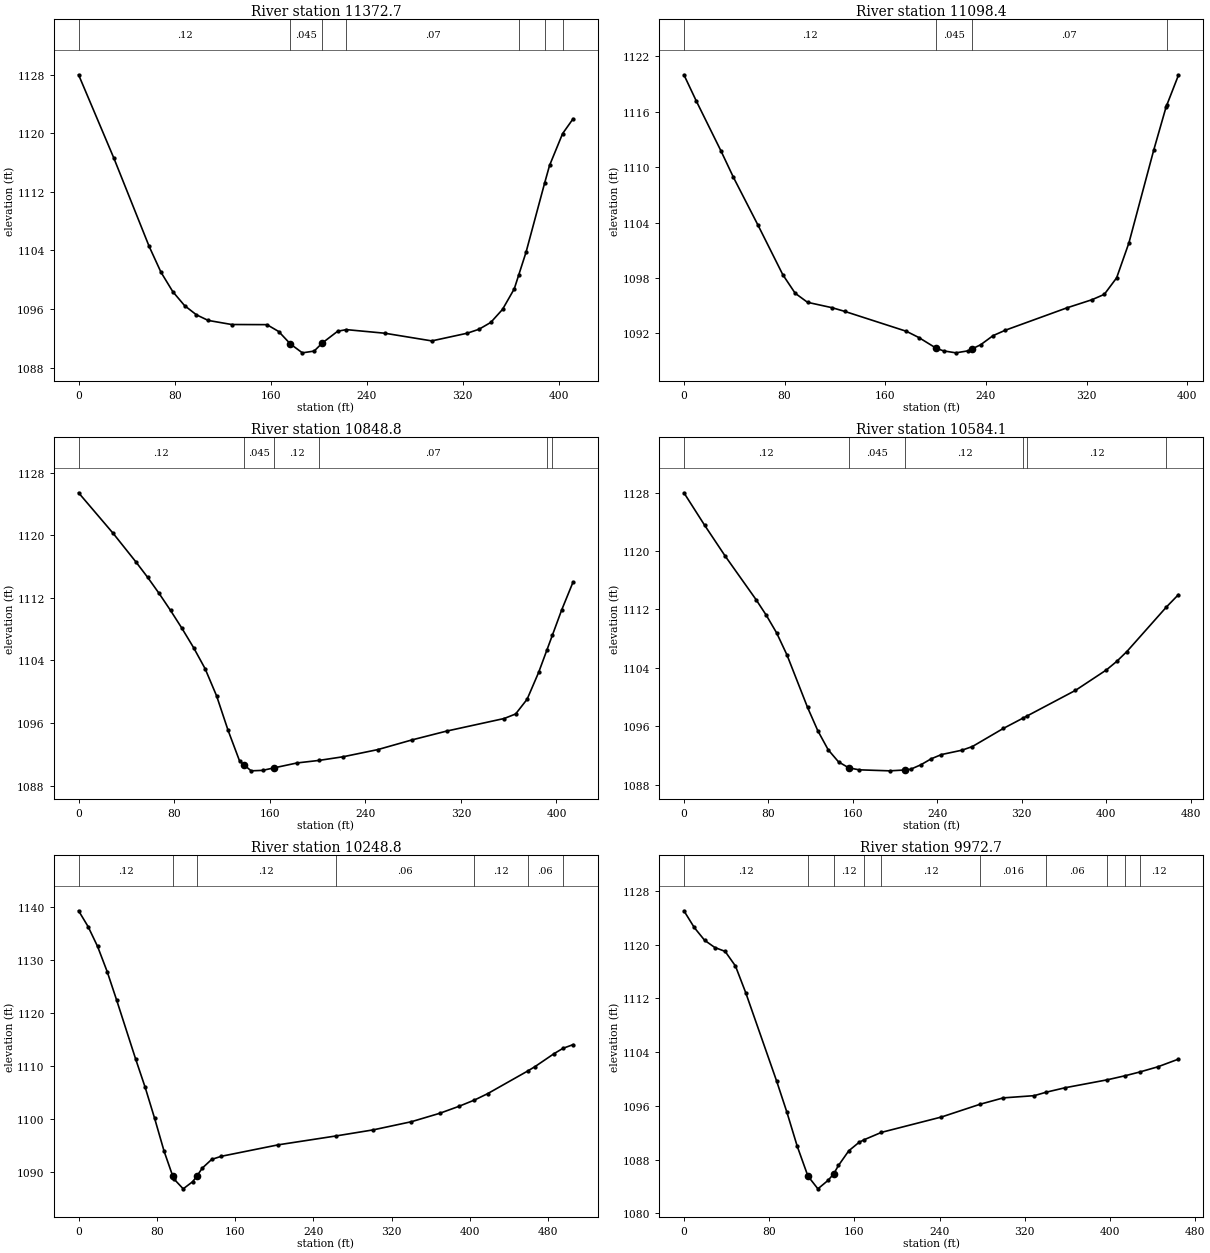
Type RM Length L Ch R = 1 ,11372.7 ,275.4,274.3,273.1
XS GIS Cut Line= 2
     1795240.324      263402.391      1795580.46      263634.755
#Sta/Elev= 30
       0    1128    29.4 1116.61    58.8 1104.55    68.6 1101.04    78.5 1098.37
    88.3 1096.47    98.1 1095.22   107.9 1094.45   127.5 1093.89   156.9 1093.87
   166.7 1092.93   176.5 1091.22   186.4 1090.02   196.2 1090.26  203.12 1091.38
   215.8 1092.97  223.031093.191     255  1092.7   294.2 1091.65   323.7  1092.7
   333.5 1093.24   343.3 1094.17   353.1 1095.95   362.9 1098.76  366.641100.668
   372.7 1103.76  388.221113.226   392.3 1115.62  403.171119.968   411.9 1121.99
#Mann= 7 ,-1 , 0
       0     .12       0   176.5    .045       0  203.12     .12       0
  223.03     .07       0  366.64     .12       0  388.22     .06       0
  403.17    .016       0
Bank Sta=176.5,203.12
XS Rating Curve= 0 ,0
Exp/Cntr=0.3,0.1

Type RM Length L Ch R = 1 ,11098.4 ,248,249.6,251.2
XS GIS Cut Line= 2
     1795092.866      263642.643     1795428.429      263847.088
#Sta/Elev= 29
       0    1120     9.8 1117.17    29.5 1111.74    39.3 1108.91    58.9 1103.71
    78.6 1098.35    88.4 1096.35    98.2 1095.37   117.9 1094.78   127.7 1094.39
   176.8 1092.23   186.6 1091.56  200.57 1090.39   206.3 1090.11   216.1  1089.9
   225.9 1090.12  228.911090.321   235.8 1090.78   245.6 1091.76   255.4 1092.35
   304.5 1094.78   324.2 1095.65     334 1096.23   343.8 1098.02   353.6 1101.82
   373.3 1111.86   383.1 1116.52  383.561116.681   392.9 1119.95
#Mann= 4 ,-1 , 0
       0     .12       0  200.57    .045       0  228.91     .07       0
  383.56    .016       0
Bank Sta=200.57,228.91
XS Rating Curve= 0 ,0
Exp/Cntr=0.3,0.1

Type RM Length L Ch R = 1 ,10848.8 ,254.9,264.7,273
XS GIS Cut Line= 2
     1794965.832      263788.888      1795314.53      264011.944
#Sta/Elev= 30
       0 1125.44    28.9 1120.26    48.1 1116.58    57.8 1114.63    67.4 1112.57
      77 1110.39    86.6 1108.09    96.3 1105.63   105.9 1102.95   115.5 1099.48
   125.1 1095.08   134.8 1091.13   138.5 1090.65   144.4 1089.89     154 1089.95
   163.6 1090.27   182.9  1090.9  201.121091.221   221.4 1091.69   250.3  1092.6
   279.2 1093.85     308 1094.97   356.2 1096.58   365.8 1097.16   375.4 1099.04
   385.1 1102.49  391.841105.277  396.551107.227   404.3 1110.44   413.9 1114.04
#Mann= 6 ,-1 , 0
       0     .12       0   138.5    .045       0   163.6     .12       0
  201.12     .07       0  391.84     .12       0  396.55    .016       0
Bank Sta=138.5,163.6
XS Rating Curve= 0 ,0
Exp/Cntr=0.3,0.1

Type RM Length L Ch R = 1 ,10584.1 ,333.4,335.3,334.3
XS GIS Cut Line= 2
      1794853.67      263885.731     1795120.457      264270.628
#Sta/Elev= 30
       0 1127.97    19.5 1123.55      39 1119.32    68.3 1113.34      78  1111.2
    87.8 1108.78    97.6 1105.76   117.1 1098.57   126.8 1095.38   136.6 1092.78
   146.4 1091.12   156.1  1090.3   165.9 1090.03   194.8 1089.89   209.8 1090.01
   214.6  1090.1   224.4 1090.72   234.2 1091.54   243.9 1092.12   263.4 1092.72
   273.2 1093.22   302.4 1095.69  321.541097.145  325.131097.416   370.8 1100.91
     400  1103.7   409.8 1104.87   419.5 1106.23  456.961112.334   468.3 1114.02
#Mann= 6 ,-1 , 0
       0     .12       0   156.1    .045       0   209.8     .12       0
  321.54     .06       0  325.13     .12       0  456.96    .016       0
Bank Sta=156.1,209.8
XS Rating Curve= 0 ,0
Exp/Cntr=0.3,0.1

Type RM Length L Ch R = 1 ,10248.8 ,281.3,276.1,270.9
XS GIS Cut Line= 2
      1794625.12      264043.879     1794931.679      264446.023
#Sta/Elev= 30
       0 1139.31     9.7 1136.33    19.4 1132.58    29.2 1127.83    38.9 1122.44
    58.4 1111.26    68.1 1105.93    77.8 1100.05    87.5 1093.83    96.2 1089.21
    97.2 1088.68     107 1086.75   116.7 1088.11  121.02 1089.17   126.4 1090.65
   136.1 1092.31   145.9  1092.9   204.2 1095.07  263.191096.746   301.4  1097.9
   340.4 1099.44   369.5 1101.04     389 1102.35  404.821103.532   418.2 1104.73
  459.171109.011   466.8 1109.86   486.2  1112.3  495.351113.309   505.7 1114.01
#Mann= 7 ,-1 , 0
       0     .12       0    96.2    .045       0  121.02     .12       0
  263.19     .06       0  404.82     .12       0  459.17     .06       0
  495.35    .016       0
Bank Sta=96.2,121.02
XS Rating Curve= 0 ,0
Exp/Cntr=0.3,0.1

Type RM Length L Ch R = 1 ,9972.7  ,262.9,252.2,241.5
XS GIS Cut Line= 2
     1794369.478      264207.074     1794727.144      264503.127
#Sta/Elev= 30
       0 1125.05     9.7 1122.56    19.4 1120.66      29 1119.58    38.7    1119
    48.4 1116.82      58 1112.86    87.1 1099.66    96.7 1095.04   106.4 1089.97
   116.4 1085.54   125.8 1083.63   135.4  1084.9  140.62 1085.86   145.1 1087.11
   154.8  1089.3   164.4 1090.55  169.151090.942   185.51092.044   241.8 1094.33
  278.271096.241   299.9 1097.18   328.9 1097.51   340.11098.024   357.9 1098.69
  397.391099.868  414.521100.488  427.861101.028     445 1101.81   464.3 1102.95
#Mann= 10 ,-1 , 0
       0     .12       0   116.4    .045       0  140.62     .12       0
  169.15    .016       0   185.5     .12       0  278.27    .016       0
   340.1     .06       0  397.39     .12       0  414.52     .08       0
  427.86     .12       0
Bank Sta=116.4,140.62
XS Rating Curve= 0 ,0
Exp/Cntr=0.3,0.1

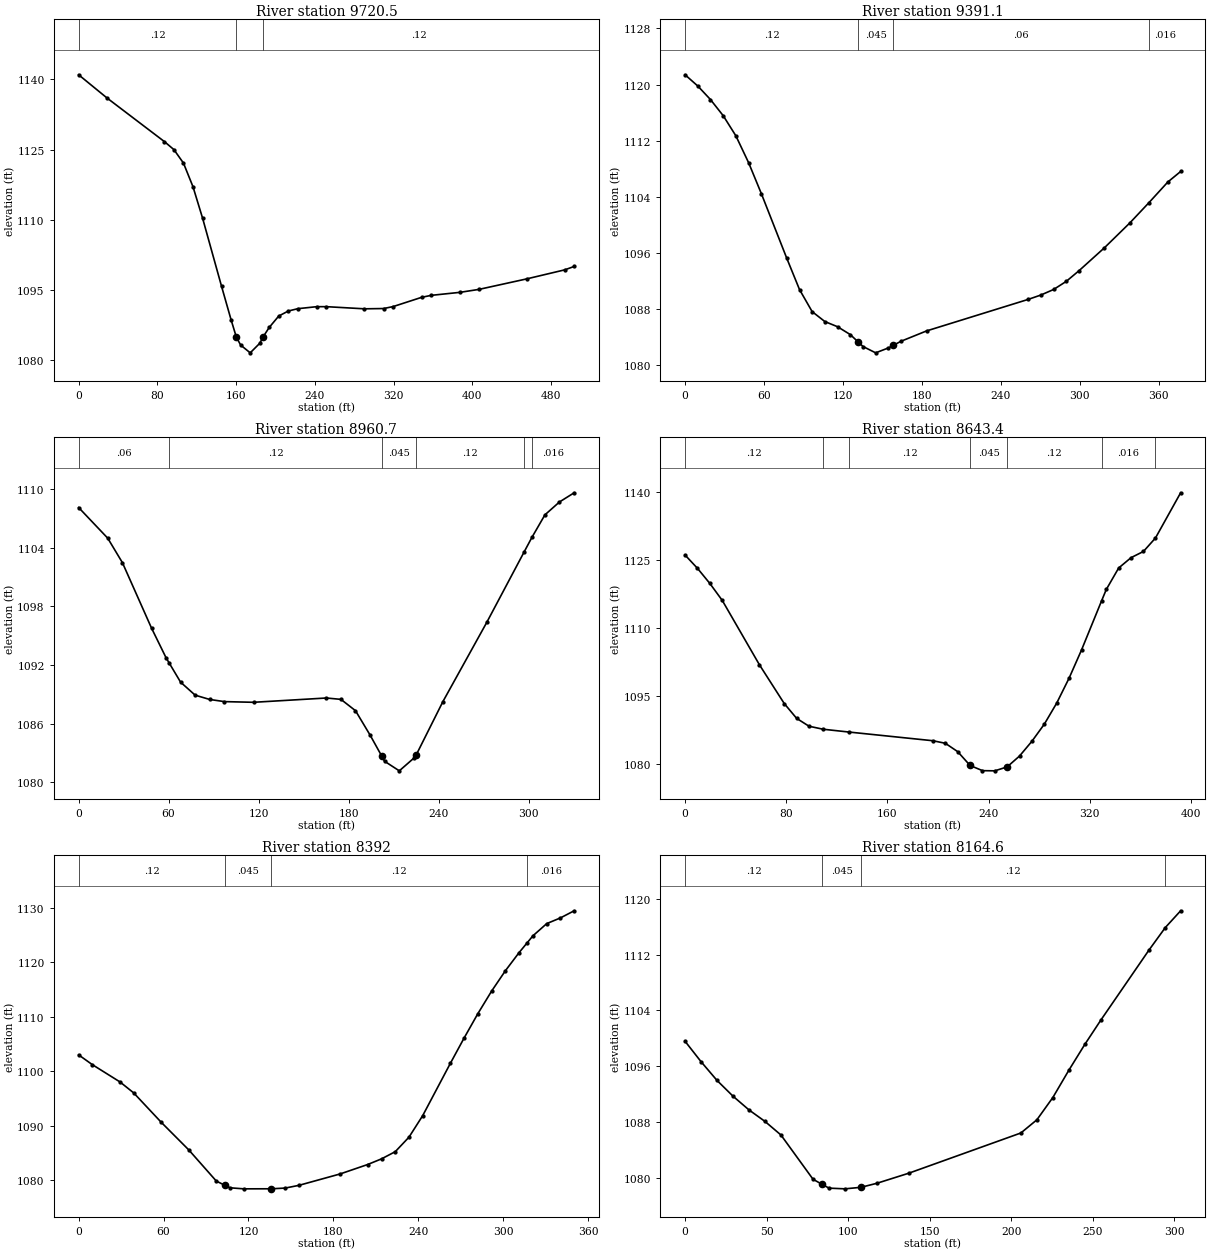
Type RM Length L Ch R = 1 ,9720.5  ,326.9,329.4,332.3
XS GIS Cut Line= 2
     1794173.948       264465.32       1794665.6      264573.645
#Sta/Elev= 30
       0 1140.99      29    1136    87.1 1126.71    96.8 1124.99   106.5 1122.11
   116.2 1117.04   125.9 1110.35   145.2 1095.76   154.9 1088.59  160.23  1084.9
   164.6 1083.21   174.3 1081.55     184 1083.59   187.5 1084.99   193.6 1086.98
   203.3 1089.42     213 1090.49   222.7 1090.99     242 1091.42   251.7 1091.42
   290.4 1090.96   309.8 1091.02   319.5 1091.44   348.5 1093.42   358.2 1093.84
   387.3 1094.48   406.6 1095.11     455 1097.35   493.8 1099.29   503.4 1100.02
#Mann= 3 ,-1 , 0
       0     .12       0  160.23    .045       0   187.5     .12       0
Bank Sta=160.23,187.5
XS Rating Curve= 0 ,0
Exp/Cntr=0.3,0.1

Type RM Length L Ch R = 1 ,9391.1  ,417.4,430.4,432.5
XS GIS Cut Line= 2
     1794137.056      264774.999     1794492.525      264899.999
#Sta/Elev= 30
       0 1121.39     9.7 1119.78    19.3 1117.86      29 1115.56    38.6  1112.7
    48.3 1108.87      58 1104.46    77.3 1095.27      87 1090.81    96.6 1087.67
   106.3 1086.25   115.9 1085.52   125.6  1084.4  131.82 1083.31   135.3  1082.7
   144.9  1081.8   154.6  1082.5  158.451082.881   164.2 1083.45   183.6 1084.92
   260.9 1089.41   270.5 1090.03   280.2 1090.82   289.8 1091.97   299.5 1093.49
   318.8 1096.75   338.2  1100.3  352.761103.193   367.1 1106.13   376.8 1107.62
#Mann= 4 ,-1 , 0
       0     .12       0  131.82    .045       0  158.45     .06       0
  352.76    .016       0
Bank Sta=131.82,158.45
XS Rating Curve= 0 ,0
Exp/Cntr=0.3,0.1

Type RM Length L Ch R = 1 ,8960.7  ,317.6,317.3,316
XS GIS Cut Line= 2
     1794025.077      264992.447     1794315.442      265149.999
#Sta/Elev= 27
       0 1108.13    19.4 1104.99    29.2 1102.48    48.6 1095.78    58.3 1092.74
   60.521092.168      68 1090.24    77.7 1088.91    87.4 1088.47    97.2 1088.25
   116.6 1088.18   165.2 1088.62   174.9 1088.48   184.6 1087.32   194.3 1084.83
   202.1 1082.67     204 1082.14   213.8 1081.16   223.5 1082.46  225.21 1082.83
   242.9 1088.26   272.1 1096.36  297.141103.611  302.191105.063   310.9 1107.38
   320.6  1108.7   330.4 1109.64
#Mann= 6 ,-1 , 0
       0     .06       0   60.52     .12       0   202.1    .045       0
  225.21     .12       0  297.14     .08       0  302.19    .016       0
Bank Sta=202.1,225.21
XS Rating Curve= 0 ,0
Exp/Cntr=0.3,0.1

Type RM Length L Ch R = 1 ,8643.4  ,239.1,251.5,262.7
XS GIS Cut Line= 2
     1793814.139      265217.707     1794163.098      265396.093
#Sta/Elev= 30
       0 1126.05     9.8 1123.12    19.6 1119.78    29.4 1116.04    58.8 1101.84
    78.4  1093.3    88.2 1090.03      98 1088.29  109.151087.629  129.721087.004
     196 1085.09   205.8 1084.53   215.6 1082.68   225.4 1079.63   235.2 1078.49
   244.9 1078.45   254.7 1079.32   264.5 1081.72   274.3 1084.98   284.1 1088.75
   293.9  1093.4   303.7 1098.91   313.5  1105.1  329.331115.921   333.1 1118.46
   342.9  1123.2   352.7 1125.48   362.5 1126.85  371.991129.813   391.9 1139.79
#Mann= 7 ,-1 , 0
       0     .12       0  109.15     .06       0  129.72     .12       0
   225.4    .045       0   254.7     .12       0  329.33    .016       0
  371.99     .12       0
Bank Sta=225.4,254.7
XS Rating Curve= 0 ,0
Exp/Cntr=0.3,0.1

Type RM Length L Ch R = 1 ,8392    ,231.3,227.3,222.2
XS GIS Cut Line= 2
     1793746.258      265304.253     1793934.626      265599.391
#Sta/Elev= 30
       0 1103.01     9.7 1101.21    29.2 1098.04    38.9 1096.02    58.4 1090.61
    77.8 1085.55    97.3 1079.81   103.1 1079.07     107 1078.58   116.7 1078.39
   136.2  1078.4   145.9 1078.53   155.6 1079.03   184.8 1081.13   204.2 1082.86
     214  1083.9   223.7 1085.22   233.4 1087.89   243.1 1091.85   262.6 1101.44
   272.3 1106.09     282 1110.56   291.8 1114.74   301.5 1118.47   311.2 1121.81
  316.951123.623     321  1124.9   330.7 1127.13   340.4 1128.18   350.1 1129.49
#Mann= 4 ,-1 , 0
       0     .12       0   103.1    .045       0   136.2     .12       0
  316.95    .016       0
Bank Sta=103.1,136.2
XS Rating Curve= 0 ,0
Exp/Cntr=0.3,0.1

Type RM Length L Ch R = 1 ,8164.6  ,280.4,272.4,264.3
XS GIS Cut Line= 2
     1793606.501      265473.957     1793813.966       265696.18
#Sta/Elev= 23
       0 1099.57     9.8 1096.64    19.6 1093.95    29.4 1091.69    39.2 1089.72
      49 1088.07    58.8 1086.12    78.5 1079.76    84.1 1079.03    88.3 1078.49
    98.1 1078.39   107.9 1078.61   117.7 1079.19   137.3 1080.64     206 1086.41
   215.8  1088.3   225.6  1091.5   235.4 1095.41   245.2 1099.12     255  1102.6
   284.4 1112.61  294.611115.905     304 1118.31
#Mann= 4 ,-1 , 0
       0     .12       0    84.1    .045       0   107.9     .12       0
  294.61    .016       0
Bank Sta=84.1,107.9
XS Rating Curve= 0 ,0
Exp/Cntr=0.3,0.1

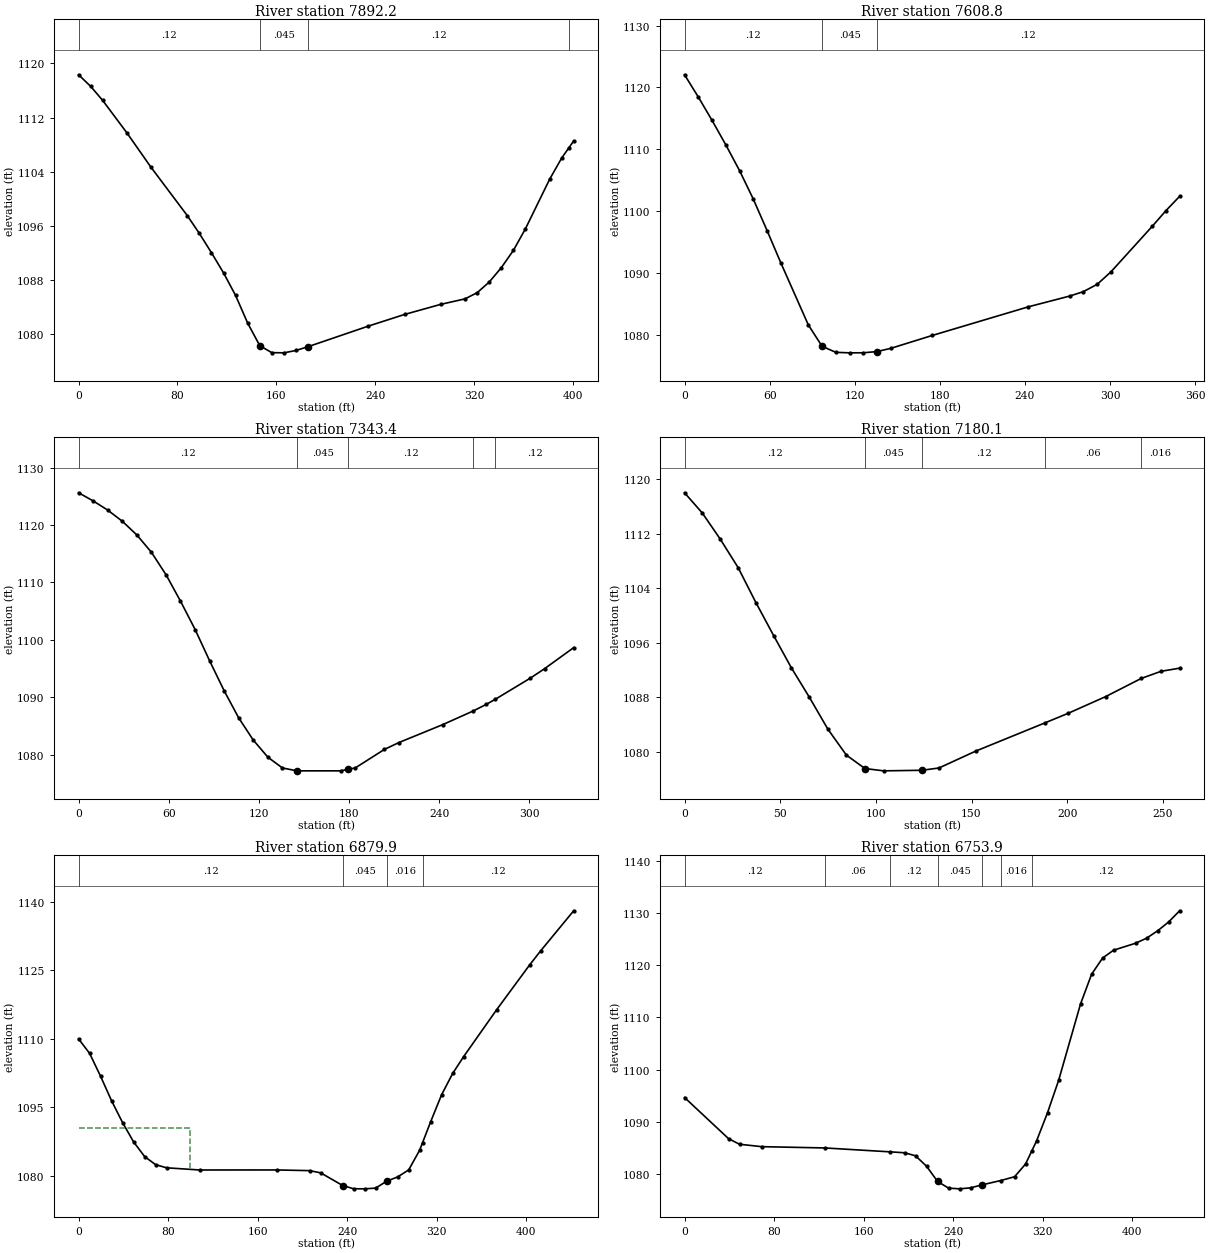
Type RM Length L Ch R = 1 ,7892.2  ,290.3,283.4,276
XS GIS Cut Line= 2
     1793370.389      265658.853     1793728.896      265837.673
#Sta/Elev= 29
       0 1118.33     9.8 1116.61    19.5 1114.54    39.1 1109.75    58.6 1104.67
    87.9 1097.55    97.7 1094.91   107.5 1092.06   117.3 1089.08     127 1085.76
   136.8 1081.67   146.6 1078.34   156.3 1077.31   166.1 1077.28   175.9 1077.63
   185.7 1078.19   234.5 1081.23   263.8 1082.95   293.1 1084.44   312.7 1085.25
   322.5 1086.16   332.2 1087.72     342 1089.84   351.8  1092.4   361.5 1095.57
   381.1 1102.89   390.9 1106.04  396.681107.542   400.6 1108.56
#Mann= 4 ,-1 , 0
       0     .12       0   146.6    .045       0   185.7     .12       0
  396.68    .016       0
Bank Sta=146.6,185.7
XS Rating Curve= 0 ,0
Exp/Cntr=0.3,0.1

Type RM Length L Ch R = 1 ,7608.8  ,264.9,265.4,265.7
XS GIS Cut Line= 2
     1793326.119      265984.374     1793671.605      266034.721
#Sta/Elev= 24
       0 1122.05     9.7 1118.46    19.4 1114.69    29.1 1110.74    38.8 1106.58
    48.5 1101.98    58.2 1096.91    67.9  1091.7    87.3 1081.68      97 1078.24
   106.7 1077.27   116.4 1077.19   126.1  1077.2   135.8  1077.4   145.5 1077.92
   174.6 1079.99   242.5 1084.62   271.6 1086.35   281.2 1087.06     291 1088.25
   300.6 1090.24   329.7 1097.58   339.4 1100.12   349.1 1102.44
#Mann= 3 ,-1 , 0
       0     .12       0      97    .045       0   135.8     .12       0
Bank Sta=97,135.8
XS Rating Curve= 0 ,0
Exp/Cntr=0.3,0.1

Type RM Length L Ch R = 1 ,7343.4  ,163.6,163.4,163.1
XS GIS Cut Line= 2
     1793290.645      266231.729     1793616.136      266283.419
#Sta/Elev= 28
       0  1125.6     9.7 1124.18    19.4 1122.58    29.1 1120.64    38.8 1118.25
    48.5 1115.23    58.2 1111.33    67.8 1106.75    77.6 1101.78    87.2 1096.36
    96.9 1091.13   106.6  1086.4   116.3 1082.54     126 1079.57   135.7 1077.69
   145.4 1077.19   174.5 1077.19   179.4 1077.45   184.2  1077.7   203.6 1080.92
   213.2 1082.11   242.3 1085.22  262.661087.607   271.4 1088.76  277.431089.649
   300.5 1093.29   310.2 1094.97   329.6 1098.64
#Mann= 5 ,-1 , 0
       0     .12       0   145.4    .045       0   179.4     .12       0
  262.66     .06       0  277.43     .12       0
Bank Sta=145.4,179.4
XS Rating Curve= 0 ,0
Exp/Cntr=0.3,0.1

Type RM Length L Ch R = 1 ,7180.1  ,277.5,300.1,322.4
XS GIS Cut Line= 3
     1793331.915      266379.724     1793388.252      266412.647
     1793579.678      266440.971
#Sta/Elev= 21
       0 1118.01     9.3 1115.03    18.6 1111.23      28 1107.02    37.3 1101.88
    46.6 1097.02    55.9 1092.27    65.2    1088    74.9  1083.3    84.6 1079.48
    94.3 1077.51     104 1077.17     124 1077.25     133 1077.59   152.3 1080.08
  188.531084.229   200.7 1085.64   220.1 1088.07   238.71090.738   249.1 1091.79
   258.8 1092.25
#Mann= 5 ,-1 , 0
       0     .12       0    94.3    .045       0     124     .12       0
  188.53     .06       0   238.7    .016       0
Bank Sta=94.3,124
XS Rating Curve= 0 ,0
Exp/Cntr=0.3,0.1

Type RM Length L Ch R = 1 ,6879.9  ,126,126,126
XS GIS Cut Line= 2
     1793222.855      266456.205     1793408.149      266857.661
#Sta/Elev= 30
       0 1109.97     9.8 1106.83    19.6 1101.83    29.5 1096.43    39.3 1091.67
    49.1 1087.47      59 1084.25    68.8 1082.48    78.6  1081.8   108.1 1081.32
   176.9 1081.33   206.3 1081.18   216.2  1080.7   235.8 1077.93   245.6 1077.22
   255.5  1077.2   265.3 1077.36   275.1 1078.86   284.9  1079.8   294.8 1081.33
   304.6 1085.64  307.24 1087.31   314.4 1091.84   324.2 1097.76   334.1 1102.42
   343.9 1106.11   373.4 1116.37   402.8 1126.14   412.7 1129.24   442.2    1138
#Mann= 4 ,-1 , 0
       0     .12       0   235.8    .045       0   275.1    .016       0
  307.24     .12       0
#XS Ineff= 2 , 0
           99.77 1090.56
Permanent Ineff=
       F       F
Bank Sta=235.8,275.1
XS Rating Curve= 0 ,0
Exp/Cntr=0.3,0.1

Type RM Length L Ch R = 1 ,6753.9  ,178.3,178.4,178.4
XS GIS Cut Line= 2
     1793114.711      266522.346     1793300.005      266923.802
#Sta/Elev= 30
       0 1094.66    39.3 1086.78    49.1 1085.71    68.8 1085.25  125.351085.002
  183.761084.253   196.5 1084.08   206.3  1083.5   216.2 1081.49     226 1078.58
   235.8 1077.31   245.6 1077.17   255.5 1077.36   265.3 1077.91  282.511078.767
   294.8 1079.49   304.6 1081.93   310.31084.495   314.4 1086.34   324.2 1091.75
   334.1 1097.93   353.7 1112.59   363.6 1118.29   373.4 1121.38   383.2 1122.88
   402.8 1124.21   412.7 1125.18   422.5 1126.59   432.3 1128.27   442.2 1130.43
#Mann= 7 ,-1 , 0
       0     .12       0  125.35     .06       0  183.76     .12       0
     226    .045       0   265.3     .08       0  282.51    .016       0
   310.3     .12       0
Bank Sta=226,265.3
XS Rating Curve= 0 ,0
Exp/Cntr=0.3,0.1

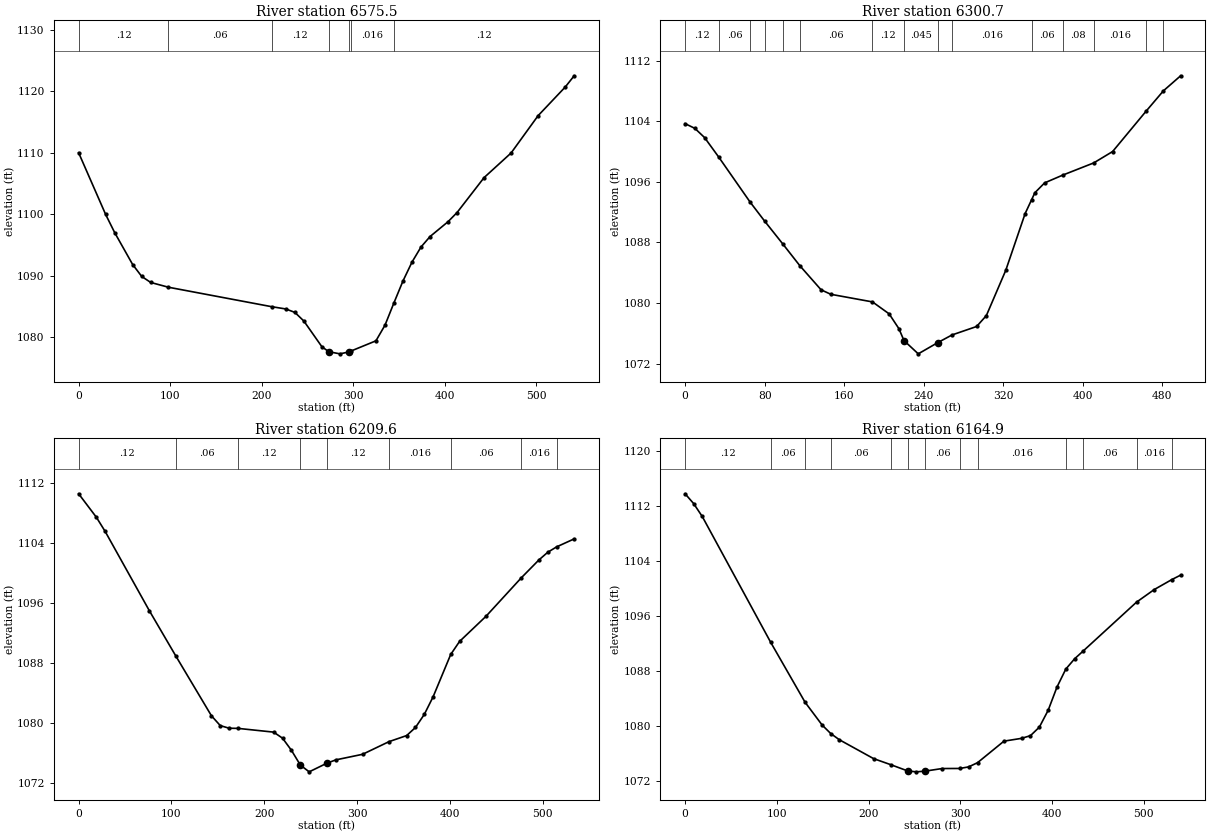
Type RM Length L Ch R = 1 ,6575.5  ,273.1,274.8,276.6
XS GIS Cut Line= 2
     1792942.583        266571.1     1793169.192      267062.586
#Sta/Elev= 30
       0    1110    29.5 1099.95    39.4 1096.98      59 1091.79    68.9 1089.85
    78.7 1088.87   98.141088.089  210.751084.923   226.3 1084.55   236.2 1083.99
     246 1082.58   265.7 1078.39   273.3 1077.58   285.4 1077.24   295.2 1077.55
  297.631077.709   324.7 1079.36   334.6 1081.91   344.21085.486   354.2  1089.1
   364.1 1092.19   373.9 1094.64   383.8 1096.35   403.4 1098.76   413.3 1100.26
   442.8 1105.95   472.3 1109.96   501.8 1116.04   531.4  1120.7   541.2 1122.54
#Mann= 7 ,-1 , 0
       0     .12       0   98.14     .06       0  210.75     .12       0
   273.3    .045       0   295.2     .12       0  297.63    .016       0
   344.2     .12       0
Bank Sta=273.3,295.2
XS Rating Curve= 0 ,0
Exp/Cntr=0.3,0.1

Type RM Length L Ch R = 1 ,6300.7  ,72.6,91.1,109.6
XS GIS Cut Line= 2
      1792720.19      266694.747     1792892.397      267162.456
#Sta/Elev= 30
       0 1103.68     9.8 1103.06    19.6 1101.84      341099.234    65.41093.322
   79.891090.831   98.111087.823  115.431084.921   136.8 1081.74   146.6 1081.15
  188.481080.145   205.2 1078.57     215 1076.62  220.17 1075.04   234.5 1073.29
   254.1 1074.77  268.511075.786   293.2  1076.9     303 1078.34   322.5 1084.31
     342 1091.81   348.51093.634   351.8 1094.56   361.6 1095.86  379.691096.879
  410.981098.496     430    1100  463.571105.313  481.081108.014   498.4    1110
#Mann= 15 ,-1 , 0
       0     .12       0      34     .06       0    65.4     .12       0
   79.89     .06       0   98.11     .08       0  115.43     .06       0
  188.48     .12       0  220.17    .045       0   254.1     .12       0
  268.51    .016       0   348.5     .06       0  379.69     .08       0
  410.98    .016       0  463.57     .12       0  481.08     .06       0
Bank Sta=220.17,254.1
XS Rating Curve= 0 ,0
Exp/Cntr=0.3,0.1

Type RM Length L Ch R = 1 ,6209.6  ,43.9,44.8,45.5
XS GIS Cut Line= 4
     1792695.459      266689.576     1792743.202      266854.506
     1792691.986      266968.221     1792751.014      267198.256
#Sta/Elev= 30
       0 1110.61    19.1 1107.48    28.6 1105.58    76.3 1094.98   104.9 1088.92
   143.1 1080.98   152.6 1079.67   162.2 1079.32   171.7  1079.3   210.1  1078.8
   219.7 1077.99   229.3 1076.37   238.9  1074.4   248.4  1073.5   267.6 1074.66
   277.2  1075.1   305.9 1075.84   334.4 1077.53   353.4 1078.34   362.9 1079.42
   372.4 1081.16   381.9 1083.51   400.9 1089.17   410.4  1090.9   438.9 1094.26
   476.9 1099.39   495.9 1101.78   505.4  1102.8   514.9 1103.52   533.9 1104.59
#Mann= 9 ,-1 , 0
       0     .12       0   104.9     .06       0   171.7     .12       0
   238.9    .045       0   267.6     .12       0   334.4    .016       0
   400.9     .06       0   476.9    .016       0   514.9     .06       0
Bank Sta=238.9,267.6
XS Rating Curve= 0 ,0
Exp/Cntr=0.3,0.1

Type RM Length L Ch R = 1 ,6164.9  ,203.1,182.3,161.2
XS GIS Cut Line= 4
     1792673.757       266696.52     1792719.764      266818.916
      1792654.66      266953.464     1792719.764      267205.201
#Sta/Elev= 30
       0 1113.73     9.3 1112.31    18.7 1110.43    93.4 1092.12   130.8 1083.43
   149.4 1080.12   158.8 1078.88   168.1 1077.99   205.5 1075.24   224.2 1074.36
   242.9 1073.44   252.2 1073.32   261.5 1073.42   280.2  1073.8   299.5 1073.81
   309.1 1074.04   318.8 1074.65   347.6 1077.78   366.9 1078.19   376.5 1078.58
   386.2 1079.82   395.8 1082.27   405.4 1085.64     415 1088.25   424.7 1089.76
   434.3 1090.92   492.1 1097.98   511.4 1099.81   530.6 1101.26   540.2 1101.91
#Mann= 13 ,-1 , 0
       0     .12       0    93.4     .06       0   130.8     .08       0
   158.8     .06       0   224.2    .016       0   242.9    .045       0
   261.5     .06       0   299.5     .08       0   318.8    .016       0
     415     .12       0   434.3     .06       0   492.1    .016       0
   530.6     .12       0
Bank Sta=242.9,261.5
XS Rating Curve= 0 ,0
Exp/Cntr=0.3,0.1