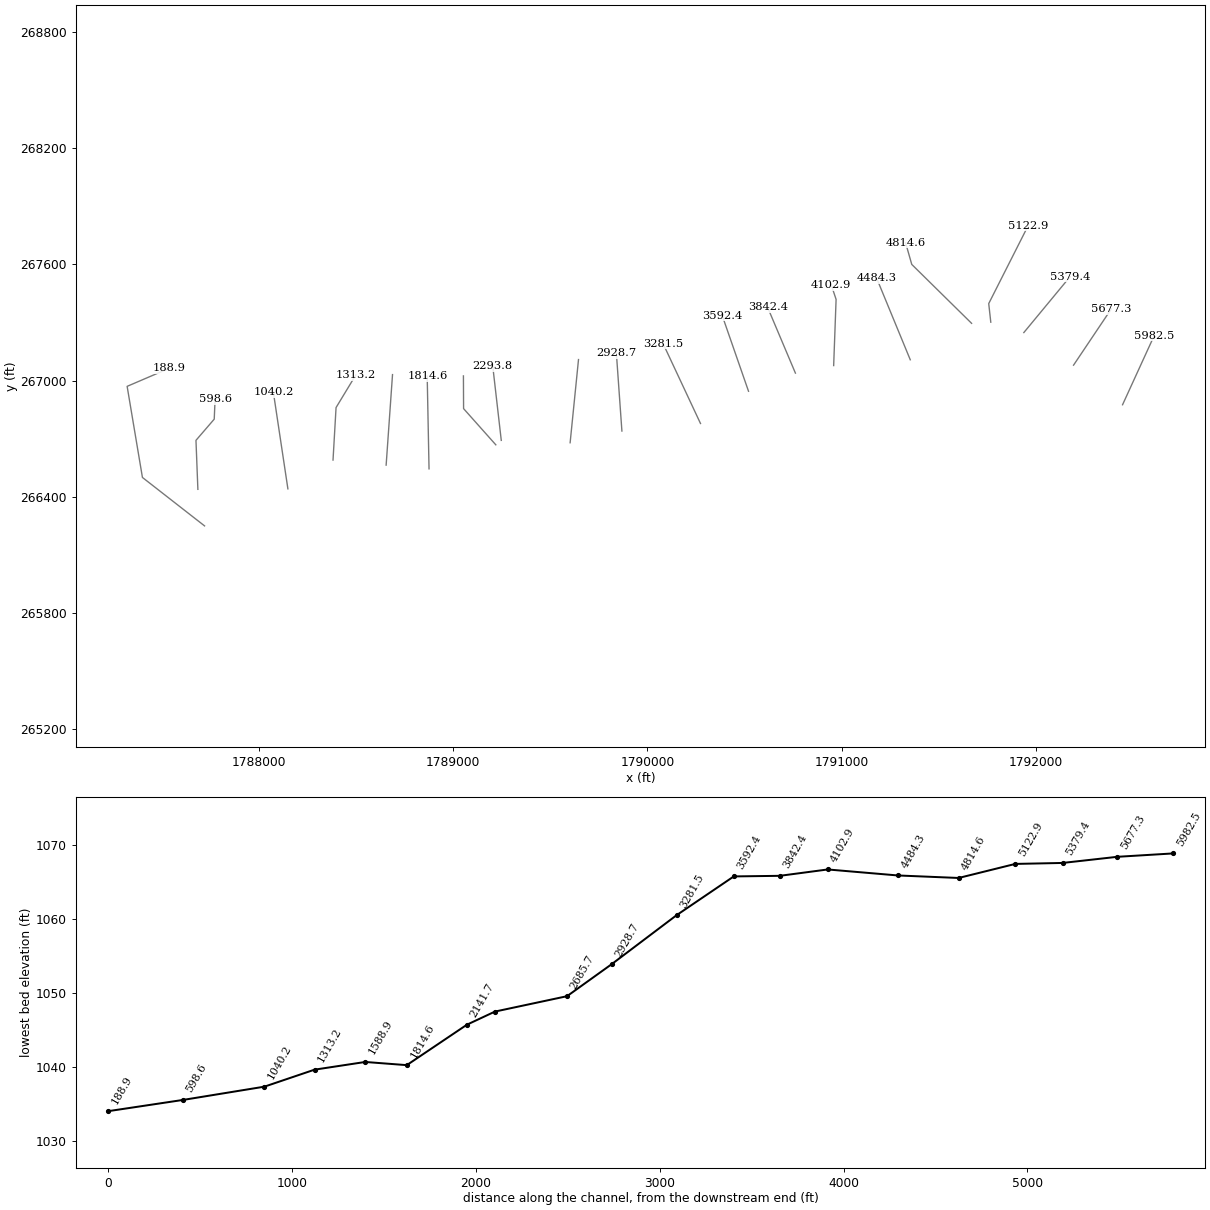
HEC-RAS study SIMPSONCK.prj: SIMPSONCK

--- SIMPSONCK.g01 (geometry) --- (continued)

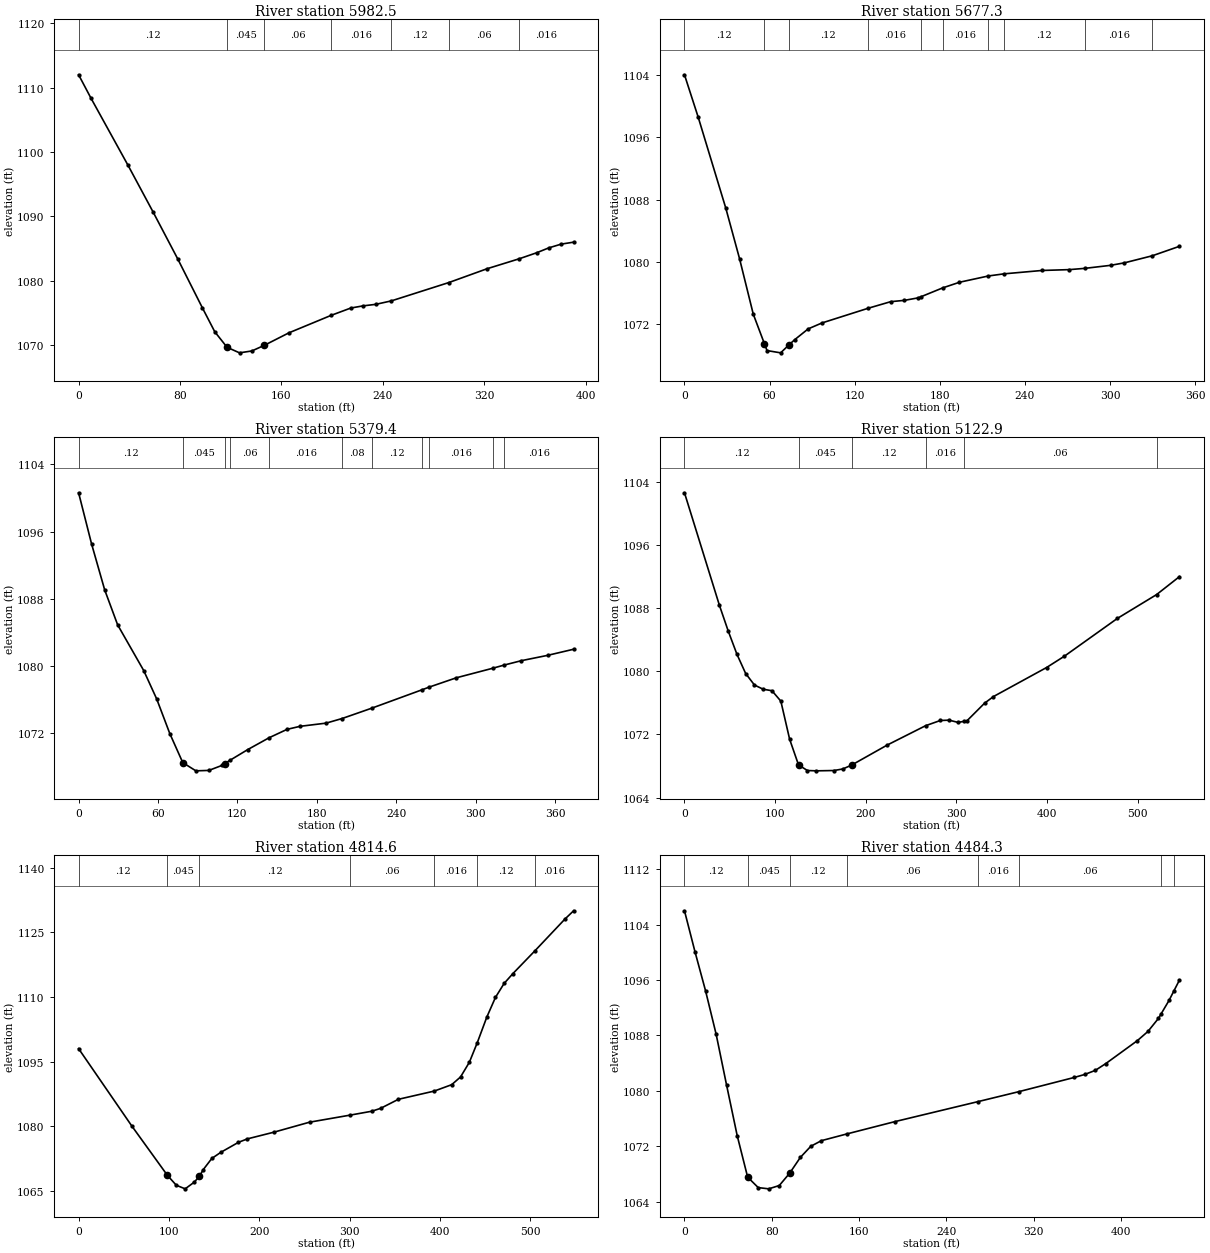
Type RM Length L Ch R = 1 ,5982.5  ,308.9,305.2,301.5
XS GIS Cut Line= 2
     1792445.856      266875.246     1792608.068      267230.396
#Sta/Elev= 24
       0    1112     9.8 1108.35      39 1097.93    58.6 1090.74    78.1 1083.43
    97.6 1075.81   107.4 1072.08   117.1 1069.67   126.9 1068.81   136.6  1069.1
   146.4 1069.97   165.9 1071.92  199.181074.633   214.7 1075.77   224.5 1076.11
   234.3 1076.34  246.631076.878  291.981079.726   322.1 1081.87  347.51 1083.42
   361.2 1084.35   370.9 1085.12   380.7  1085.7   390.4    1086
#Mann= 7 ,-1 , 0
       0     .12       0   117.1    .045       0   146.4     .06       0
  199.18    .016       0  246.63     .12       0  291.98     .06       0
  347.51    .016       0
Bank Sta=117.1,146.4
XS Rating Curve= 0 ,0
Exp/Cntr=0.3,0.1

Type RM Length L Ch R = 1 ,5677.3  ,300.1,297.9,295.6
XS GIS Cut Line= 2
     1792193.578       267079.48     1792387.745      267369.441
#Sta/Elev= 28
       0    1104     9.7 1098.55    29.1 1086.92    38.8 1080.44    48.5 1073.31
   56.32 1069.54    58.2 1068.64    67.8 1068.35   73.38 1069.32    77.6 1070.02
    87.2 1071.42    96.9 1072.18  129.591074.071   145.4 1074.91   155.1 1075.08
   164.8  1075.4  166.921075.555  182.011076.675   193.9  1077.4  214.271078.205
   225.31078.478     252 1078.91   271.4 1079.02  282.271079.181   300.5 1079.57
   310.2 1079.89  329.831080.794     349 1082.01
#Mann= 10 ,-1 , 0
       0     .12       0   56.32    .045       0   73.38     .12       0
  129.59    .016       0  166.92     .12       0  182.01    .016       0
  214.27     .06       0   225.3     .12       0  282.27    .016       0
  329.83     .12       0
Bank Sta=56.32,73.38
XS Rating Curve= 0 ,0
Exp/Cntr=0.3,0.1

Type RM Length L Ch R = 1 ,5379.4  ,251.2,256.5,261.2
XS GIS Cut Line= 2
     1791937.638      267247.554     1792175.702      267535.961
#Sta/Elev= 28
       0 1100.63     9.8 1094.54    19.7 1089.07    29.5  1084.9    49.2 1079.46
      59 1076.08    68.9 1071.96    78.7  1068.5    88.6 1067.52    98.4 1067.57
   108.2 1068.16   110.5 1068.39  114.261068.766   127.9 1070.06  143.961071.462
   157.5 1072.46   167.3 1072.82     187  1073.2  199.121073.752  221.511074.983
  259.291077.161  264.761077.484   285.4  1078.6  313.061079.743  321.511080.114
   334.6 1080.64   354.3 1081.27     374    1082
#Mann= 11 ,-1 , 0
       0     .12       0    78.7    .045       0   110.5     .12       0
  114.26     .06       0  143.96    .016       0  199.12     .08       0
  221.51     .12       0  259.29     .08       0  264.76    .016       0
  313.06     .08       0  321.51    .016       0
Bank Sta=78.7,110.5
XS Rating Curve= 0 ,0
Exp/Cntr=0.3,0.1

Type RM Length L Ch R = 1 ,5122.9  ,278.7,308.3,336.9
XS GIS Cut Line= 3
     1791767.499      267301.157       1791756.9      267397.063
     1791959.462      267798.338
#Sta/Elev= 30
       0 1102.62    38.6 1088.34    48.2 1085.12    57.9 1082.15    67.5 1079.72
    77.2 1078.26    86.8 1077.73    96.5 1077.54   106.3 1076.22     116 1071.39
   125.8 1068.14   135.6 1067.43   145.4 1067.39   164.9 1067.43   174.7 1067.63
   184.4 1068.12   223.5 1070.65  265.971073.109   282.2 1073.77   291.9 1073.81
   301.7 1073.53  307.951073.651   311.5 1073.72     331 1075.96   340.8  1076.8
   399.4 1080.48     419 1081.91   477.6 1086.71  520.691089.716     546    1092
#Mann= 6 ,-1 , 0
       0     .12       0   125.8    .045       0   184.4     .12       0
  265.97    .016       0  307.95     .06       0  520.69    .016       0
Bank Sta=125.8,184.4
XS Rating Curve= 0 ,0
Exp/Cntr=0.3,0.1

Type RM Length L Ch R = 1 ,4814.6  ,339.4,330.4,321.3
XS GIS Cut Line= 3
     1791668.689      267295.238     1791360.677      267599.191
     1791329.103      267710.194
#Sta/Elev= 30
       0 1098.01      59 1080.04    98.4  1068.6   108.2 1066.32     118 1065.49
   127.8    1067  133.81 1068.38   137.7 1069.86   147.5 1072.54   157.4 1073.95
     177 1076.28   186.9 1077.08   216.4 1078.64   255.7 1080.95  300.841082.597
   324.6 1083.49   334.4 1084.16   354.1 1086.26  393.85 1088.17   413.1 1089.65
   422.9 1091.44   432.7 1094.86  441.471099.408     452 1105.33   461.6 1109.91
   471.2 1113.15   480.8  1115.4  505.461120.746   538.5 1128.07   548.1 1129.99
#Mann= 7 ,-1 , 0
       0     .12       0    98.4    .045       0  133.81     .12       0
  300.84     .06       0  393.85    .016       0  441.47     .12       0
  505.46    .016       0
Bank Sta=98.4,133.81
XS Rating Curve= 0 ,0
Exp/Cntr=0.3,0.1

Type RM Length L Ch R = 1 ,4484.3  ,390.9,381.3,371.6
XS GIS Cut Line= 2
     1791352.993      267107.209     1791180.434       267526.84
#Sta/Elev= 29
       0    1106     9.6  1100.1    19.3 1094.45      29 1088.18    38.6 1080.81
    48.3 1073.53    57.9 1067.52    67.6 1066.01    77.2 1065.83    86.9 1066.31
    96.5 1068.11   106.2 1070.37   115.8 1071.98   125.5 1072.79   148.71073.757
   193.1 1075.55   269.11078.433   306.31079.862   357.2 1081.92   366.8 1082.35
   376.5 1082.94   386.2 1083.93   415.1 1087.24   424.8 1088.57   434.4 1090.45
  436.811091.094   444.1 1093.04  448.38 1094.36   453.7    1096
#Mann= 8 ,-1 , 0
       0     .12       0    57.9    .045       0    96.5     .12       0
   148.7     .06       0   269.1    .016       0   306.3     .06       0
  436.81     .12       0  448.38    .016       0
Bank Sta=57.9,96.5
XS Rating Curve= 0 ,0
Exp/Cntr=0.3,0.1

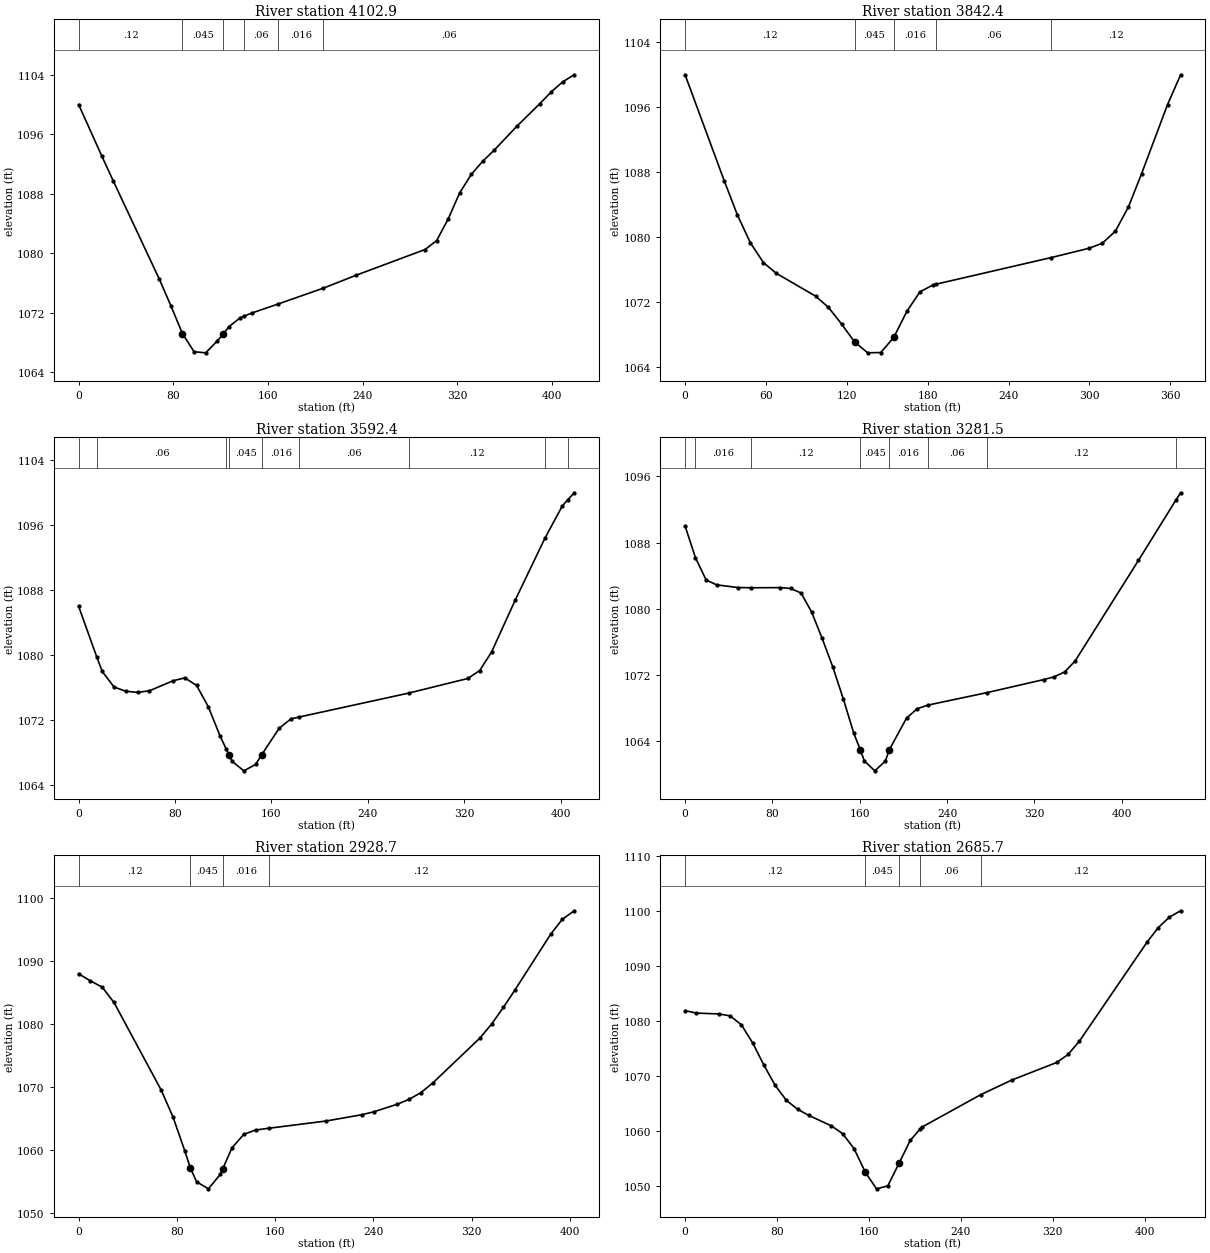
Type RM Length L Ch R = 1 ,4102.9  ,250.6,260.6,270.3
XS GIS Cut Line= 3
     1790958.655       267077.33     1790971.182      267418.758
      1790946.81      267492.093
#Sta/Elev= 29
       0    1100    19.5 1093.11    29.3 1089.73    68.3 1076.51    78.1 1072.92
    87.8 1069.21    97.6 1066.79   107.4 1066.64   117.1 1068.22  122.16 1069.13
   126.9 1070.14   136.7 1071.36  139.771071.559   146.4 1071.99  168.351073.184
  206.931075.334   234.3 1077.05   292.8 1080.52   302.6 1081.71   312.4 1084.63
   322.1 1088.13   331.9 1090.61   341.7  1092.4   351.3 1093.87   370.6 1097.11
     390 1100.14   399.6 1101.72   409.3 1103.06   418.9    1104
#Mann= 6 ,-1 , 0
       0     .12       0    87.8    .045       0  122.16     .12       0
  139.77     .06       0  168.35    .016       0  206.93     .06       0
Bank Sta=87.8,122.16
XS Rating Curve= 0 ,0
Exp/Cntr=0.3,0.1

Type RM Length L Ch R = 1 ,3842.4  ,251.4,250,248.5
XS GIS Cut Line= 2
     1790761.739      267038.455     1790618.848      267377.286
#Sta/Elev= 25
       0    1100      29 1086.97    38.7 1082.79    48.4 1079.33    58.1 1076.89
    67.7 1075.56    96.8 1072.76   106.4 1071.37   116.1 1069.33   125.8 1067.11
   135.5 1065.78   145.2 1065.82   154.8 1067.67   164.5 1070.87   174.2 1073.28
   183.9 1074.13  186.131074.225  271.751077.508     300 1078.66   309.7 1079.28
   319.3 1080.76     329 1083.75   338.7 1087.82     358 1096.34   367.7    1100
#Mann= 5 ,-1 , 0
       0     .12       0   125.8    .045       0   154.8    .016       0
  186.13     .06       0  271.75     .12       0
Bank Sta=125.8,154.8
XS Rating Curve= 0 ,0
Exp/Cntr=0.3,0.1

Type RM Length L Ch R = 1 ,3592.4  ,308.4,310.9,313.1
XS GIS Cut Line= 2
     1790520.351      266944.905     1790385.588      267333.459
#Sta/Elev= 30
       0    1086   15.011079.768    19.6 1077.96    29.4 1076.04    39.2 1075.52
      49 1075.38    58.8 1075.58    78.3 1076.81    88.1 1077.17    97.9 1076.24
   107.7 1073.59   117.5 1069.96  122.431068.416  125.051067.595   127.3 1066.89
   137.1  1065.7   146.9 1066.49  151.99  1067.7   166.5 1070.96   176.2 1072.11
  183.251072.347  274.451075.309   323.1  1077.1   332.9 1078.08   342.7 1080.35
   362.3 1086.74  386.931094.379   401.5  1098.4  405.831099.111   411.3 1100.01
#Mann= 9 ,-1 , 0
       0     .12       0   15.01     .06       0  122.43     .12       0
  125.05    .045       0  151.99    .016       0  183.25     .06       0
  274.45     .12       0  386.93     .06       0  405.83    .016       0
Bank Sta=125.05,151.99
XS Rating Curve= 0 ,0
Exp/Cntr=0.3,0.1

Type RM Length L Ch R = 1 ,3281.5  ,361.1,352.8,344.6
XS GIS Cut Line= 2
     1790273.088      266778.592     1790080.944      267189.802
#Sta/Elev= 30
       0 1089.99    9.451086.181    19.3 1083.47      29 1082.89    48.3 1082.57
    60.41082.543    86.9 1082.56    96.6 1082.46   106.2 1081.91   115.9 1079.61
   125.5 1076.45   135.2 1073.02   144.9 1069.15   154.5    1065  160.51 1062.99
   164.2 1061.65   173.8 1060.46   183.5 1061.65  186.79 1062.94   202.8 1066.82
   212.5 1067.94  222.161068.382  276.35 1069.89   328.3 1071.46     338  1071.8
   347.7 1072.39   357.3 1073.72   415.3 1085.85  449.341093.074   453.9    1094
#Mann= 8 ,-1 , 0
       0     .12       0    9.45    .016       0    60.4     .12       0
  160.51    .045       0  186.79    .016       0  222.16     .06       0
  276.35     .12       0  449.34     .06       0
Bank Sta=160.51,186.79
XS Rating Curve= 0 ,0
Exp/Cntr=0.3,0.1

Type RM Length L Ch R = 1 ,2928.7  ,246.8,242.9,239.1
XS GIS Cut Line= 2
     1789868.546      266739.648     1789839.994      267142.216
#Sta/Elev= 30
       0 1087.99     9.6 1086.87    19.2 1085.87    28.8 1083.44    67.3  1069.5
    76.9 1065.23    86.5 1059.85   90.91  1057.2    96.1 1054.96   105.7 1053.84
   115.3 1056.12  117.391057.041   124.9 1060.35   134.5 1062.49   144.1 1063.18
  154.761063.457   201.8 1064.62   230.6 1065.61   240.2 1066.06   259.4 1067.27
     269 1068.04   278.7 1069.11   288.3 1070.63   326.7 1077.76   336.3    1080
   345.9 1082.64   355.5 1085.46   384.4 1094.26     394 1096.66   403.6    1098
#Mann= 4 ,-1 , 0
       0     .12       0   90.91    .045       0  117.39    .016       0
  154.76     .12       0
Bank Sta=90.91,117.39
XS Rating Curve= 0 ,0
Exp/Cntr=0.3,0.1

Type RM Length L Ch R = 1 ,2685.7  ,387.1,391.9,396.7
XS GIS Cut Line= 2
     1789601.975      266679.238     1789645.129      267108.349
#Sta/Elev= 30
       0 1081.87     9.8 1081.42    29.4 1081.27    39.2 1080.92      49 1079.29
    58.8 1076.02    68.6 1071.97    78.4 1068.29    88.2 1065.57      98 1063.95
   107.8 1062.83   127.4 1060.94   137.2 1059.51     147 1056.83   156.8 1052.54
   166.6 1049.51   176.4 1050.04   186.2 1054.15     196 1058.31  204.781060.433
   205.8 1060.68  257.471066.627   284.2 1069.25   323.5 1072.46   333.3 1073.91
   343.1  1076.3   401.9 1094.25   411.7 1096.92   421.5 1098.85   431.3    1100
#Mann= 5 ,-1 , 0
       0     .12       0   156.8    .045       0   186.2     .12       0
  204.78     .06       0  257.47     .12       0
Bank Sta=156.8,186.2
XS Rating Curve= 0 ,0
Exp/Cntr=0.3,0.1

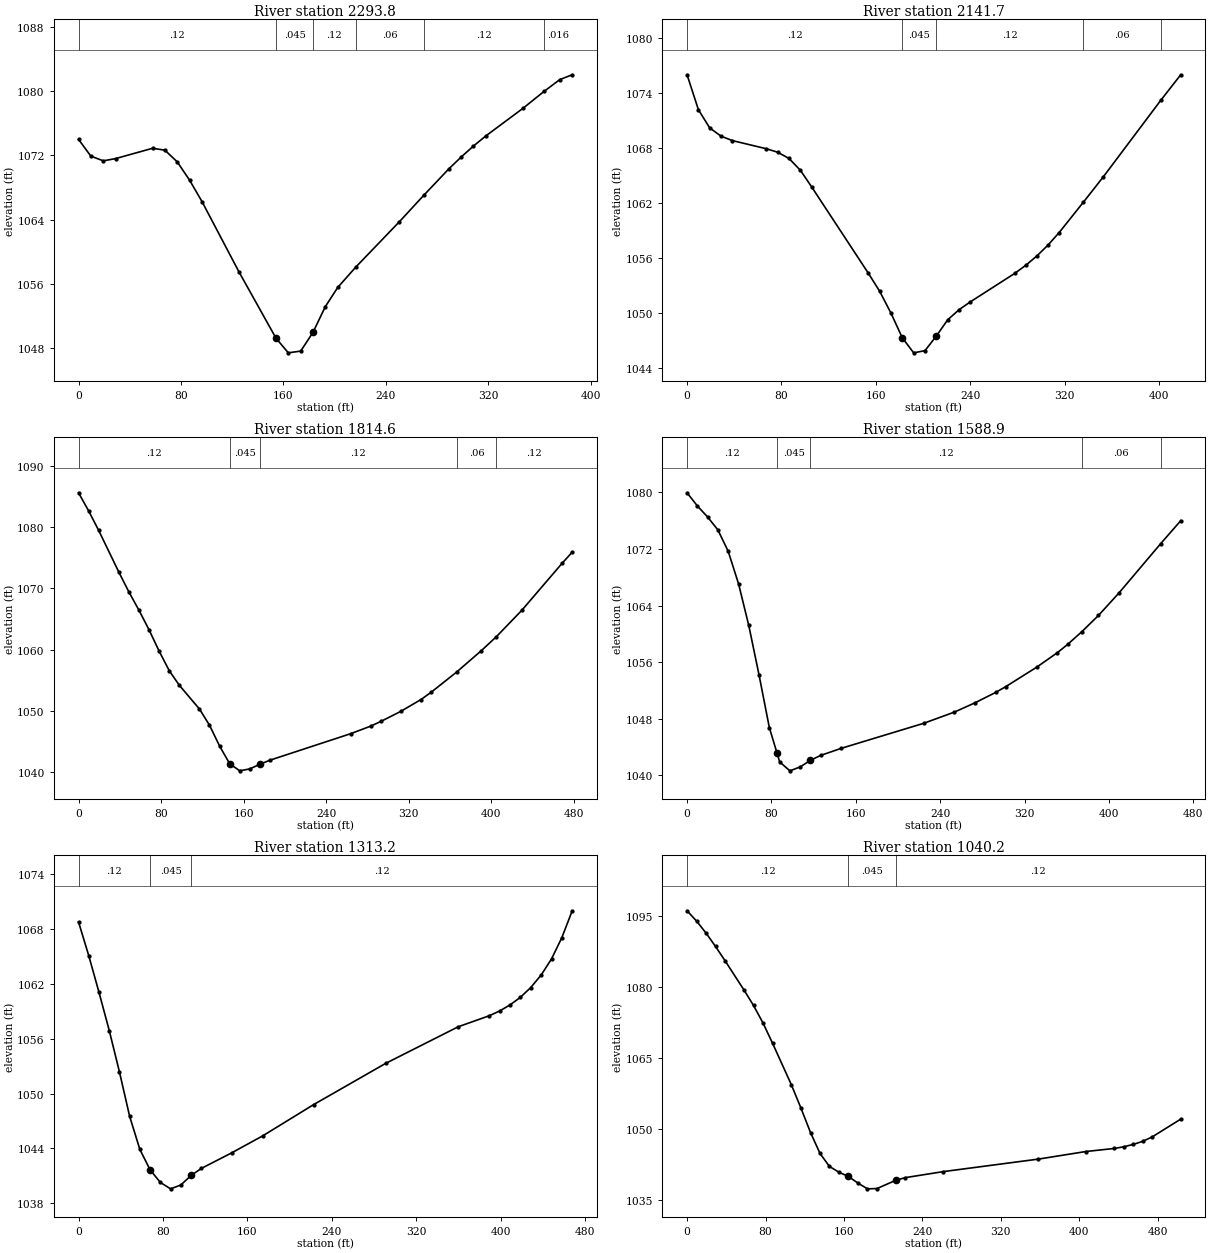
Type RM Length L Ch R = 1 ,2293.8  ,138.2,152.2,166.2
XS GIS Cut Line= 2
     1789247.528      266691.375     1789203.686      267074.329
#Sta/Elev= 27
       0 1073.97     9.6 1071.89    19.3  1071.3    28.9 1071.58    57.8 1072.86
    67.4 1072.63    77.1 1071.17    86.7  1068.9    96.4 1066.24   125.3 1057.49
   154.2 1049.25   163.8 1047.43   173.5 1047.65   183.1 1049.98   192.7 1053.17
   202.4 1055.56  216.331058.061   250.6 1063.74  269.721067.036   289.1 1070.29
   298.7 1071.76   308.4 1073.14     318 1074.39   346.9 1077.81  363.541079.934
   375.8  1081.4   385.5    1082
#Mann= 6 ,-1 , 0
       0     .12       0   154.2    .045       0   183.1     .12       0
  216.33     .06       0  269.72     .12       0  363.54    .016       0
Bank Sta=154.2,183.1
XS Rating Curve= 0 ,0
Exp/Cntr=0.3,0.1

Type RM Length L Ch R = 1 ,2141.7  ,344.1,327.1,308.3
XS GIS Cut Line= 3
     1789219.388      266668.553     1789053.502      266855.248
     1789052.692      267024.006
#Sta/Elev= 29
       0    1076     9.6 1072.19    19.2  1070.2    28.8  1069.3    38.4 1068.82
    67.2 1067.93    76.8 1067.55    86.4 1066.87    96.1 1065.57   105.7 1063.75
   153.7 1054.34   163.3 1052.37   172.9 1049.98   182.5 1047.29   192.1 1045.66
   201.7  1045.9   211.3 1047.49   220.9 1049.26   230.5 1050.36   240.1 1051.22
   277.9 1054.34   287.2 1055.22   296.6 1056.24     306 1057.42   315.4 1058.78
  336.061062.111   352.9 1064.87  401.741073.243   418.5    1076
#Mann= 5 ,-1 , 0
       0     .12       0   182.5    .045       0   211.3     .12       0
  336.06     .06       0  401.74     .12       0
Bank Sta=182.5,211.3
XS Rating Curve= 0 ,0
Exp/Cntr=0.3,0.1

Type RM Length L Ch R = 1 ,1814.6  ,227,225.6,223.2
XS GIS Cut Line= 2
     1788875.673      266544.603      1788866.18      267022.883
#Sta/Elev= 30
       0  1085.6     9.8 1082.64    19.5 1079.46      39 1072.66    48.8  1069.4
    58.6 1066.41    68.3 1063.23    78.1 1059.74    87.9 1056.55    97.6 1054.18
   117.2 1050.28   126.9 1047.65   136.7 1044.24   146.4 1041.37   156.2 1040.19
     166 1040.51   175.7 1041.26   185.5 1041.93   263.6 1046.25   283.1 1047.49
   292.9 1048.25   312.4 1049.91   331.9 1051.84   341.7 1053.02  366.451056.328
   390.5 1059.84  404.711062.062   429.6 1066.41   468.6 1074.08   478.4  1075.9
#Mann= 5 ,-1 , 0
       0     .12       0   146.4    .045       0   175.7     .12       0
  366.45     .06       0  404.71     .12       0
Bank Sta=146.4,175.7
XS Rating Curve= 0 ,0
Exp/Cntr=0.3,0.1

Type RM Length L Ch R = 1 ,1588.9  ,275.4,275.7,276
XS GIS Cut Line= 2
      1788654.84       266563.83     1788687.672      267030.757
#Sta/Elev= 29
       0 1079.95     9.8 1078.08    19.5 1076.52    29.2  1074.7      39 1071.67
    48.8 1067.08    58.5 1061.18    68.3 1054.14      78 1046.74    85.2 1043.17
    87.8 1041.88    97.5 1040.62   107.3 1041.18     117 1042.11   126.8 1042.81
   146.3 1043.81   224.3 1047.34   253.5 1048.93     273 1050.24   292.6 1051.71
   302.3 1052.54   331.6 1055.29   351.1 1057.33   360.8  1058.5  374.241060.287
   390.1  1062.6   409.6 1065.79  449.111072.759   468.1    1076
#Mann= 5 ,-1 , 0
       0     .12       0    85.2    .045       0     117     .12       0
  374.24     .06       0  449.11     .12       0
Bank Sta=85.2,117
XS Rating Curve= 0 ,0
Exp/Cntr=0.3,0.1

Type RM Length L Ch R = 1 ,1313.2  ,268.4,273,277.7
XS GIS Cut Line= 3
     1788381.402      266589.872     1788397.027      266860.705
     1788498.699      267028.791
#Sta/Elev= 27
       0 1068.78     9.7 1065.08    19.4 1061.07    29.1  1056.9    38.8 1052.35
    48.4 1047.52    58.1 1043.89    67.8 1041.66    77.5 1040.28    87.2 1039.58
    96.9    1040   106.6 1041.04   116.3 1041.81   145.3 1043.53   174.4 1045.37
   222.8  1048.8   290.9  1053.3   359.7 1057.31   389.2 1058.52     399 1059.04
   408.8  1059.7   418.6 1060.53   428.4  1061.6   438.3 1062.97   448.1 1064.73
   457.9 1067.06   467.7    1070
#Mann= 3 ,-1 , 0
       0     .12       0    67.8    .045       0   106.6     .12       0
Bank Sta=67.8,106.6
XS Rating Curve= 0 ,0
Exp/Cntr=0.3,0.1

Type RM Length L Ch R = 1 ,1040.2  ,460.7,441.6,421.8
XS GIS Cut Line= 2
     1788149.092      266441.386     1788074.357      266939.348
#Sta/Elev= 30
       0    1096     9.7 1093.82    19.4 1091.28      29 1088.47    38.7 1085.46
    58.1 1079.25    67.8    1076    77.5 1072.28    87.2 1068.02   106.5  1059.2
   116.2  1054.3   125.9 1049.17   135.6 1044.75   145.2 1042.01   154.9 1040.79
   164.6 1039.89   174.3 1038.49     184 1037.28   193.7 1037.34     213  1039.1
   222.7 1039.65   261.4 1040.92   358.3 1043.56   406.7 1045.16   435.8 1045.81
   445.4 1046.16   455.1 1046.66   464.8 1047.32   474.5 1048.26   503.5    1052
#Mann= 3 ,-1 , 0
       0     .12       0   164.6    .045       0     213     .12       0
Bank Sta=164.6,213
XS Rating Curve= 0 ,0
Exp/Cntr=0.3,0.1

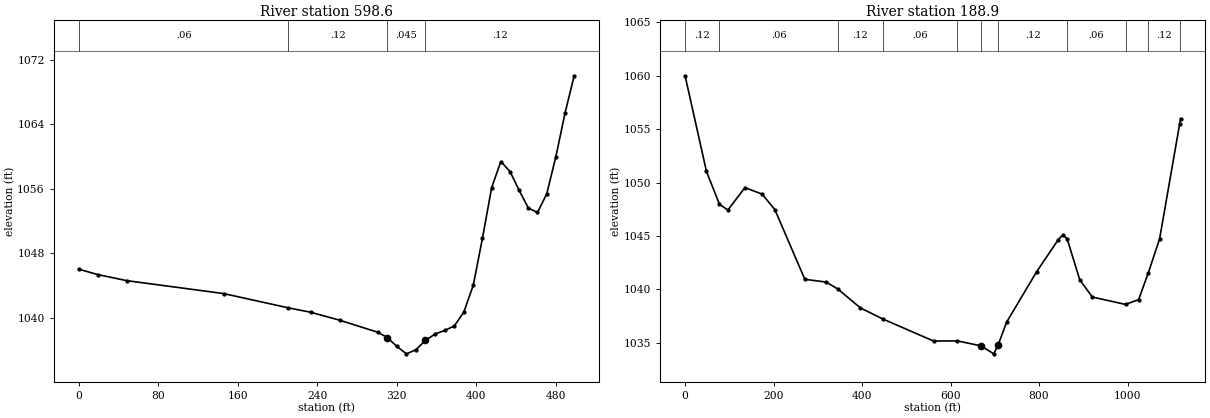
Type RM Length L Ch R = 1 ,598.6   ,388.3,409.7,429.5
XS GIS Cut Line= 4
     1787685.704       266438.87     1787675.862        266691.6
     1787769.853       266800.94     1787774.287      266902.375
#Sta/Elev= 29
       0    1046    19.5 1045.32    48.6 1044.57   145.9 1042.97   210.81041.203
   233.5 1040.65   262.5 1039.67     301 1038.17   310.6 1037.51   320.2 1036.41
   329.8 1035.49   339.4    1036     349 1037.16   358.7 1037.95   368.3 1038.39
   377.9 1038.94   387.5 1040.65   397.1 1044.01   406.3 1049.83   415.6 1056.13
   424.8 1059.35     434 1058.12   443.3 1055.77   452.5 1053.58   461.7 1053.04
     471 1055.34   480.2 1059.98   489.4 1065.37   498.6    1070
#Mann= 4 ,-1 , 0
       0     .06       0   210.8     .12       0   310.6    .045       0
     349     .12       0
Bank Sta=310.6,349
XS Rating Curve= 0 ,0
Exp/Cntr=0.3,0.1

Type RM Length L Ch R = 1 ,188.9   ,183.8,188.9,193.5
XS GIS Cut Line= 4
     1787720.151      266250.248     1787400.271      266500.161
     1787321.531      266970.146     1787539.861      267064.048
#Sta/Elev= 30
       0    1060    48.3 1051.04   77.571047.976    96.6 1047.42   135.3 1049.53
     174 1048.92     203 1047.46   270.6 1040.94     319 1040.68   344.81040.044
   396.3 1038.26  446.341037.235   561.5 1035.16  615.581035.171   668.5 1034.71
   697.7 1033.96   707.4 1034.78   726.9 1036.94   794.9 1041.67   843.6 1044.66
   853.3 1045.08  863.441044.753     892  1040.9   920.5 1039.28  995.611038.587
  1025.1 1039.04 1047.061041.548  1072.6 1044.74 1117.851055.483  1120.1 1055.99
#Mann= 11 ,-1 , 0
       0     .12       0   77.57     .06       0   344.8     .12       0
  446.34     .06       0  615.58     .12       0   668.5    .045       0
   707.4     .12       0  863.44     .06       0  995.61    .016       0
 1047.06     .12       0 1117.85    .016       0
Bank Sta=668.5,707.4
XS Rating Curve= 0 ,0
Exp/Cntr=0.3,0.1

Chan Stop Cuts=-1
Use User Specified Reach Order=0
Composite Channel Slope=5